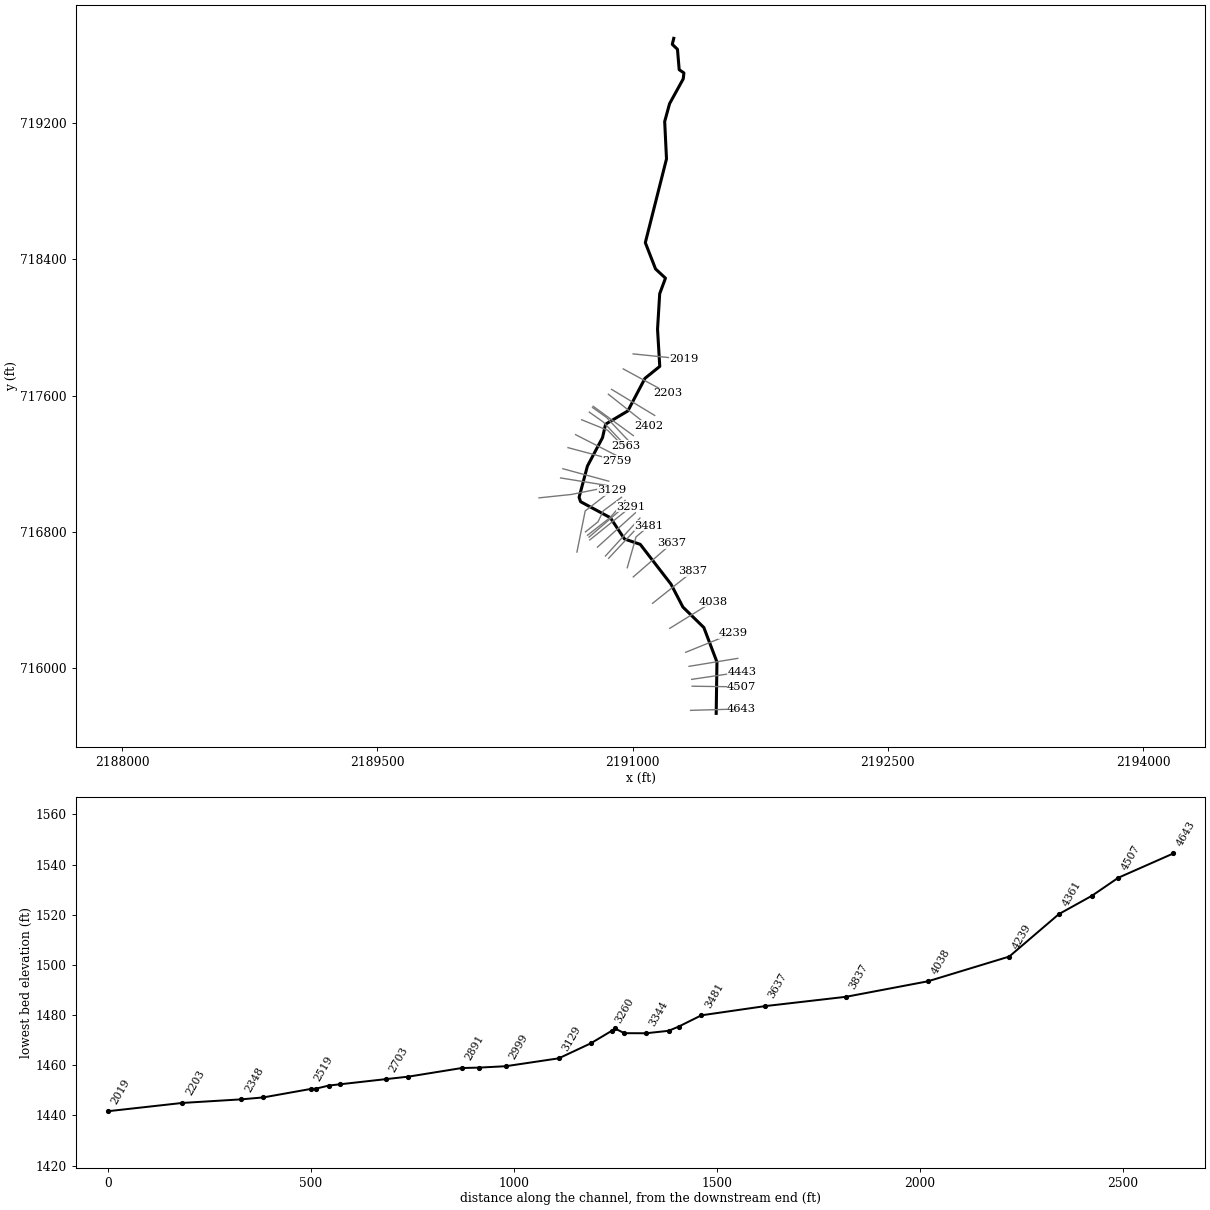
--- LISANDRNTR.prj (project) ---

Proj Title=LISANDRNTR
Current Plan=p01
Default Exp/Contr=0.3,0.1
English Units
Geom File=g01
Flow File=f01
Plan File=p01
Y Axis Title=Elevation
X Axis Title(PF)=Main Channel Distance
X Axis Title(XS)=Station
BEGIN DESCRIPTION:
---------- MODELED AS PART OF WVEMD CTP PROGRAM, 2023----------
Stream Name: Little Sand Run Tributary
Flood Zone:  AFH
Upshur County, WV
HEC-RAS Version: RAS 6.3
Vertical Datum: NAVD88
Projection: NAD 1983 StatePlane West Virginia S FIPS 4702 (US Feet)
Terrain: 1-meter LIDAR (FEMA Region III 3DEP collected 2016-2018)
Land Use: 2019 NLCD
Hydrologic Method:
WV SIR2010-5033 regression equations
Additional Model Notes:
None
END DESCRIPTION:
DSS Export Rating Curves= 0
DSS Export Rating Curve Sorted= 0
DSS Export Volume Flow Curves= 0
DXF OffsetX= 0
DXF OffsetY= 0
DXF ScaleX= 1
DXF ScaleY= 10

--- LISANDRNTR.p01 (plan) ---

Plan Title=Floodplain
Program Version=6.31
Short Identifier=Floodplain
Geom File=g01
Flow File=f01
Subcritical Flow
K Sum by GR= 0
Std Step Tol= 0.01
Critical Tol= 0.01
Num of Std Step Trials= 20
Max Error Tol= 0.3
Flow Tol Ratio= 0.001
Split Flow NTrial= 30
Split Flow Tol= 0.02
Split Flow Ratio= 0.02
Log Output Level= 0
Friction Slope Method= 1
Unsteady Friction Slope Method= 2
Unsteady Bridges Friction Slope Method= 1
Parabolic Critical Depth
Global Vel Dist= 0 , 0 , 0
Global Log Level= 0
CheckData=True
Encroach Param=-1 ,0,0, 0
Computation Interval=1MIN
Output Interval=1HOUR
Instantaneous Interval=1HOUR
Mapping Interval=1HOUR
Computation Time Step Use Courant=        0
Computation Time Step Use Time Series=    0
Computation Time Step Count To Double=0
Computation Time Step Max Doubling=0
Computation Time Step Max Halving=0
Computation Time Step Residence Courant=0
Run HTab= 0
Run UNet= 0
Run Sediment= 0
Run PostProcess= 0
Run WQNet= 0
Run RASMapper=-1
UNET Theta= 1
UNET Theta Warmup= 1
UNET ZTol= 0.02
UNET ZSATol= 0.02
UNET MxIter= 20
UNET Max Iter WO Improvement= 0
UNET MaxInSteps= 0
UNET DtIC= 0
UNET DtMin= 0
UNET MaxCRTS= 20
UNET WFStab= 2
UNET SFStab= 1
UNET WFX= 1
UNET SFX= 1
UNET Gravity=32.17405
UNET 1D Methodology=Finite Difference
UNET DSS MLevel= 4
UNET Pardiso=0
UNET DZMax Abort= 100
UNET Use Existing IB Tables=-1
UNET Froude Reduction=False
UNET Froude Limit= 0.8
UNET Froude Power= 4
UNET D1 Cores= 0
UNET WindReference=Eulerian
UNET WindDragFormulation=Hsu (1988)
UNET D2 Coriolis=0
UNET D2 Cores= 0
UNET D2 Theta= 1
UNET D2 Theta Warmup= 1
UNET D2 Z Tol= 0.01
UNET D2 Volume Tol= 0.01
UNET D2 Max Iterations= 20
UNET D2 Equation= 0
UNET D2 RampUpFraction=0.1
UNET D2 TimeSlices= 1
UNET D2 Turbulence Formulation=None
UNET D2 Eddy Viscosity=0.3
UNET D2 Transverse Eddy Viscosity=0.1
UNET D2 Smagorinsky Mixing=0.05
UNET D2 BCVolumeCheck=0
UNET D2 Cores=0
UNET D2 SolverType=PARDISO (Direct)
UNET D2 Minimum Iterations= 3
UNET D2 Maximum Iterations= 30
UNET D2 Restart Number= 10
UNET D2 Relaxation Coeff=1.3
UNET D2 SOR Precondition Iterations= 10
UNET D2 ILUT Maximum Fill= 8
UNET D2 ILUT Tolerance=1E-08
UNET D2 Convergence Tolerance=0.00001
UNET D1D2 MaxIter= 0
UNET D1D2 ZTol=0.01
UNET D1D2 QTol=0.1
UNET D1D2 MinQTol=1
Write IC File= 0
Write IC File at Fixed DateTime=0
Write IC File at Sim End=0
Echo Input=False
Echo Parameters=False
Echo Output=False
Write Detailed= 0
HDF Write Warmup=0
HDF Write Time Slices=0
HDF Flush=0
HDF Compression= 1
HDF Chunk Size= 1
HDF Spatial Parts= 1
HDF Use Max Rows=0
HDF Fixed Rows= 1
Calibration Method= 0
Calibration Iterations= 20
Calibration Max Change=0.05
Calibration Tolerance=0.2
Calibration Maximum=1.5
Calibration Minimum=0.5
Calibration Optimization Method= 1
WQ AD Non Conservative
WQ ULTIMATE=-1
WQ Max Comp Step=1HOUR
WQ Output Interval=15MIN
WQ Output Selected Increments= 0
WQ Create Restart=0
WQ Fixed Restart=0
WQ System Summary=0
WQ Write To DSS=0
Sorting and Armoring Iterations= 10
XS Update Threshold= 0.02
Bed Roughness Predictor= 0
Hydraulics Update Threshold= 0.02
Energy Slope Method= 1
Volume Change Method= 1
Sediment Retention Method= 0
Sediment TS Multiplier= 1
Warm Up Method= 0
XS Weighting Method= 0
Number of US Weighted Cross Sections= 1
Number of DS Weighted Cross Sections= 1
Upstream XS Weight=0
Main XS Weight=1
Downstream XS Weight=0
Number of DS XS's Weighted with US Boundary= 1
Upstream Boundary Weight= 1
Weight of XSs Associated with US Boundary= 0
Number of US XS's Weighted with DS Boundary= 1
Downstream Boundary Weight= 0.5
Weight of XSs Associated with DS Boundary= 0.5
Percentile Method= 0
Sediment Output Level= 3
Mass or Volume Output= 0
Output Increment Type= 1
Profile and TS Output Increment= 1
Transport Output Increment 1
XS Output Flag= 0
XS Output Increment= 10
Read HDF5 Sediment Hotstart= 0
Sediment Hotstart Type= 0
Write Gradation File= 0
Read Gradation Hotstart= 0
Write HDF5 File= 1
Write Binary Output= 1
Write DSS Sediment File= 0
DSS Sediment Output Type= 1
SV Curve= 0
Specific Gage Flag= 0
Subcell Erosion Methods= 0
Subcell Deposition Methods= 0
Advection Scheme= 1
Matrix Solver= 0
Implicit Weighting Factor= 1
Maximum Outer Loop Convergence Iterations= 5
Convergence Maximum Absolute= 0.001
Convergence RMSE= 0.0001
Grain Fractions Max Abs Error= 0.001
Max Subgrid Regions= 1
Max Subgrid Length Scale= 3.402823E+38
Initial Layer Thickness= 3.402823E+38
Min Layer Thickness= 3.402823E+38
Max Layer Thickness= 3.402823E+38
Number of Layers= 5

--- LISANDRNTR.f01 (steady flow) ---

Flow Title=Flow
Program Version=6.31
Number of Profiles= 1
Profile Names=01pct
River Rch & RM=River 1,Reach 1         ,4643
    96.3
River Rch & RM=LISANDRNTR,Main            ,4643
    96.3
Boundary for River Rch & Prof#=LISANDRNTR,Main            , 1
Up Type= 0
Dn Type= 3
Dn Slope=0.01215
DSS Import GetInterval= 0
DSS Import GetPeak= 0
DSS Import FillOption= 0

--- LISANDRNTR.g01 (geometry) ---

Geom Title=Geometry
Program Version=6.31

River Reach=LISANDRNTR      ,Main
Reach XY= 30
2191491.06837226715732.1932687612191495.48660881716034.127202573
2191418.58557759716236.5334674272191295.53759147716356.774957055
2191225.44324733716491.5247553442191044.76115739716725.429726252
 2190952.3696465716756.7748810052190869.13854731716881.900418626
2190694.34679601 716976.011812812190685.37796396717001.775504037
2190734.48753634717185.594561428  2190823.115968717352.347836837
2190841.17170617717431.5146732632190971.81416142717509.263533503
2191072.64951293717700.9616630132191159.47684383717771.090765759
2191146.38369417717989.2474816742191159.03262355718197.865767565
2191192.96767268718289.5731686482191134.73177482718343.653996517
2191074.59545192718498.1450859162191199.07453367718990.332749844
2191188.39738968719209.8638068442191217.14733218  719314.9331505
2191297.22558409719460.2458520082191301.39224242719495.445584759
2191273.61441085719514.5426594172191263.54520525719634.334414586
2191232.98949209 719663.50102292 2191241.6922306719698.777527168

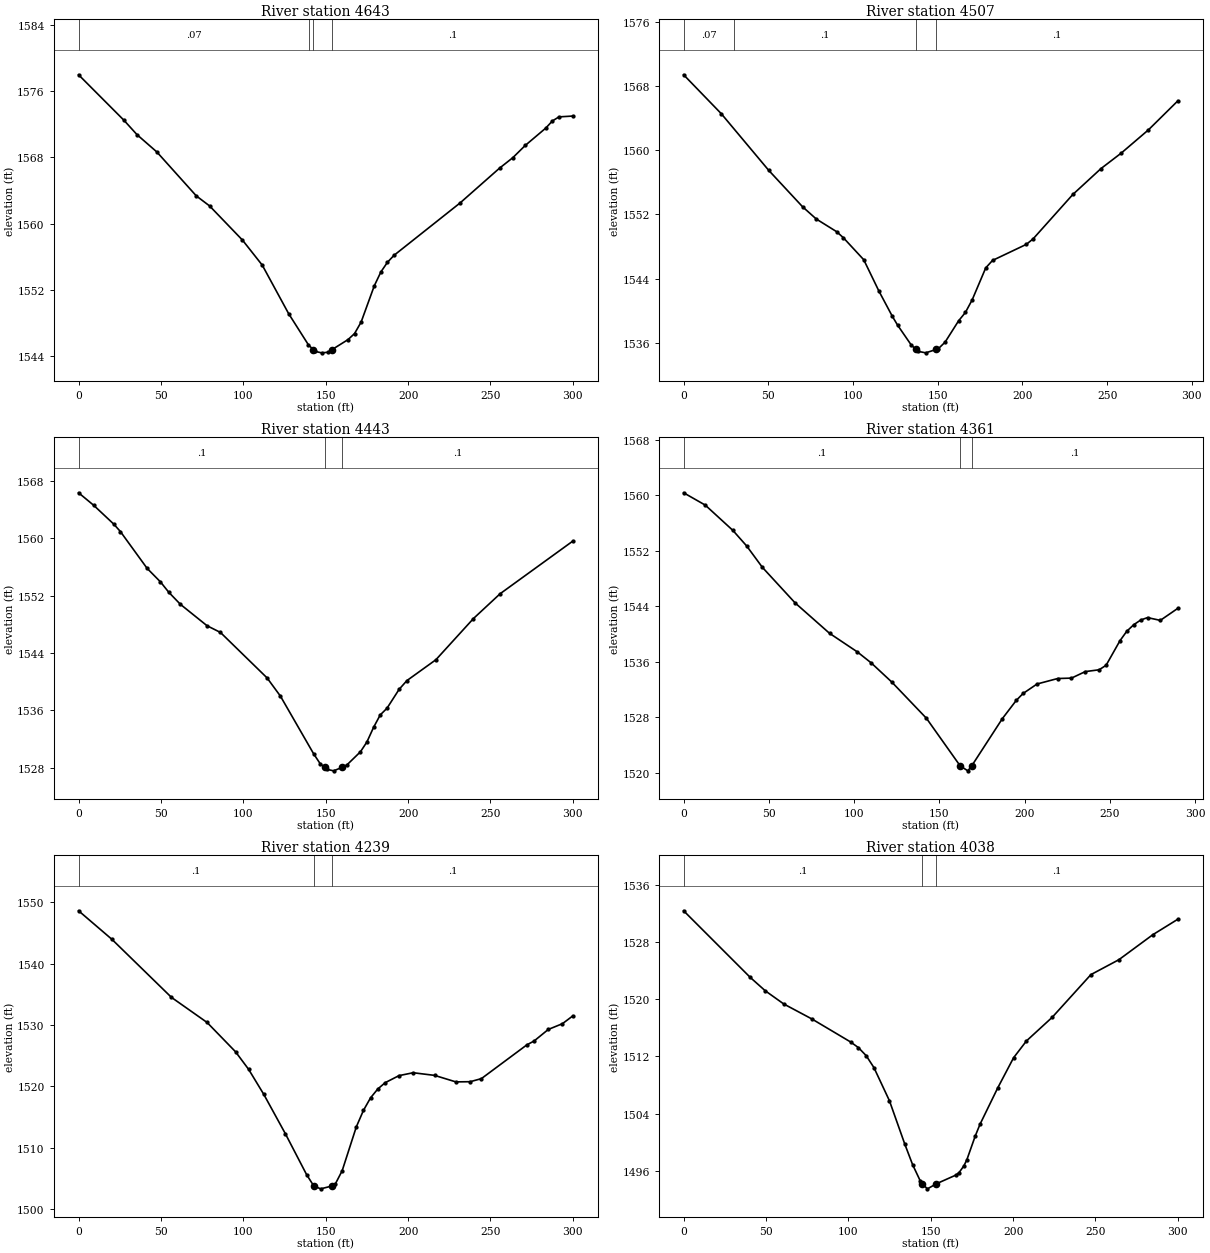
Type RM Length L Ch R = 1 ,4643    ,135.8,135.8,135.8
XS GIS Cut Line= 2
2191340.71468213715749.8966374162191640.59227959715758.465566333
#Sta/Elev= 30
       0 1577.98    27.5  1572.5    35.5 1570.75    47.5 1568.67    71.5 1563.36
    79.5 1562.16    99.5 1558.03   111.5 1555.01   127.5 1549.16   139.5  1545.4
   142.41544.827   143.5 1544.61   147.5 1544.43   151.5  1544.5   153.91544.827
   163.5 1546.02   167.5 1546.75   171.5 1548.14   179.5 1552.52   183.5 1554.19
   187.5 1555.36   191.5  1556.2   231.6 1562.52   255.5 1566.71   263.6 1567.98
   271.1 1569.45   283.6 1571.55   287.6 1572.41   291.6  1572.9     300    1573
#Mann= 4 ,-1,0
       0     .07       0     140      .1       0   142.4    .045       0
   153.9      .1       0
Bank Sta=142.4,153.9
XS Rating Curve= 0 ,0
Exp/Cntr(USF)=0,0
Exp/Cntr=0.3,0.1

Type RM Length L Ch R = 1 ,4507    ,64.8,64.8,64.8
XS GIS Cut Line= 2
2191349.93171038715891.7737104072191641.59210867715887.800135498
#Sta/Elev= 30
       0 1569.43    22.2 1564.58    50.2 1557.51    70.2 1552.96    78.3 1551.43
    90.3 1549.85    94.3 1549.09   106.3 1546.35   115.3 1542.42   123.2 1539.28
   126.3 1538.18   134.3 1535.72   137.11535.156   138.3 1534.92   142.9 1534.73
   149.21535.162   150.3 1535.24   154.3 1536.06   162.3 1538.73   166.3 1539.77
   170.3 1541.34   178.3 1545.33   182.3 1546.26   202.3 1548.27   206.3 1548.96
   229.7 1554.49   246.3 1557.72   258.3 1559.66   274.3 1562.55   291.7 1566.18
#Mann= 4 ,-1,0
       0     .07       0      30      .1       0   137.1    .045       0
   149.2      .1       0
Bank Sta=137.1,149.2
XS Rating Curve= 0 ,0
Exp/Cntr(USF)=0,0
Exp/Cntr=0.3,0.1

Type RM Length L Ch R = 1 ,4443    ,81.3,81.3,81.3
XS GIS Cut Line= 2
  2191347.027481715932.0432958012191643.78969236715975.999978019
#Sta/Elev= 30
       0 1566.35     9.2  1564.6    21.4 1561.97    25.4 1560.94    41.6 1555.81
    49.7 1553.92    54.8 1552.46    61.8 1550.79      78  1547.8    86.1 1546.87
   114.4 1540.53   122.5 1537.99   142.7 1529.93   146.7 1528.54   149.31528.052
   150.8 1527.77   154.8 1527.56     160 1528.05   162.9 1528.39   171.1 1530.22
     175 1531.58   179.1 1533.64   183.1 1535.36   187.2 1536.29   194.6 1538.94
   199.3 1540.15   216.9 1543.06   239.7 1548.81   255.9 1552.27     300 1559.61
#Mann= 3 ,-1,0
       0      .1       0   149.3    .045       0     160      .1       0
Bank Sta=149.3,160
XS Rating Curve= 0 ,0
Exp/Cntr(USF)=0,0
Exp/Cntr=0.3,0.1

Type RM Length L Ch R = 1 ,4361    ,122.4,122.4,122.4
XS GIS Cut Line= 2
 2191331.6532658716008.5968127232191617.75065922716055.484996645
#Sta/Elev= 30
       0 1560.38    12.7  1558.6    28.9 1554.95      37  1552.7    46.2 1549.62
    65.4 1544.49    85.6  1540.1   101.9 1537.42     110 1535.84   122.1 1533.07
   142.4 1527.85   162.21520.982   166.7 1520.26     1691520.984     187 1527.81
   195.1 1530.42   199.1 1531.42   207.3 1532.79   219.4 1533.58   227.5 1533.64
   235.6 1534.58   243.7 1534.84   247.8 1535.49   255.9 1539.02   259.9 1540.39
     264 1541.34   268.1 1542.02   272.1 1542.37   279.6 1541.97   289.9 1543.71
#Mann= 3 ,-1,0
       0      .1       0   162.2    .045       0     169      .1       0
Bank Sta=162.2,169
XS Rating Curve= 0 ,0
Exp/Cntr(USF)=0,0
Exp/Cntr=0.3,0.1

Type RM Length L Ch R = 1 ,4239    ,200.3,200.3,200.3
XS GIS Cut Line= 2
2191311.86961917716091.1254323622191589.97410372716203.632746238
#Sta/Elev= 30
       0 1548.61    20.2 1543.97    56.4  1534.5      78 1530.42    95.3 1525.64
   103.2 1522.79   112.4 1518.72   125.5 1512.31   138.4 1505.64   142.81503.778
     147 1503.32   153.81503.783   155.7 1504.04     160 1506.27   168.6 1513.42
   172.9 1516.09   177.2 1518.13   181.6 1519.58   186.1 1520.61   194.5 1521.76
   203.1 1522.23   216.1  1521.8     229 1520.74   237.7 1520.77   244.5 1521.27
   272.1 1526.77   276.5  1527.4   285.1 1529.28   293.7 1530.22     300 1531.49
#Mann= 3 ,-1,0
       0      .1       0   142.8    .045       0   153.8      .1       0
Bank Sta=142.8,153.8
XS Rating Curve= 0 ,0
Exp/Cntr(USF)=0,0
Exp/Cntr=0.3,0.1

Type RM Length L Ch R = 1 ,4038    ,201.3,201.3,201.3
XS GIS Cut Line= 2
2191217.99271148716231.6498830492191473.09601863716389.517874368
#Sta/Elev= 30
       0 1532.39    40.5 1523.05    49.6 1521.18    60.8 1519.34    77.8 1517.25
   101.3 1514.03   106.1 1513.23   110.8 1512.11   115.5 1510.44   124.9 1505.81
   134.3 1499.69     139 1496.84   143.7 1494.54   144.81494.171     148 1493.46
   153.41494.167   165.4  1495.4   167.2 1495.74   170.1 1496.67   171.9 1497.52
     177 1500.85   179.9  1502.5   190.7 1507.61   200.3 1511.82   208.1 1514.17
   223.7 1517.47   247.2 1523.45   264.2 1525.54   284.8 1529.04     300 1531.21
#Mann= 3 ,-1,0
       0      .1       0   144.8    .045       0   153.4      .1       0
Bank Sta=144.8,153.4
XS Rating Curve= 0 ,0
Exp/Cntr(USF)=0,0
Exp/Cntr=0.3,0.1

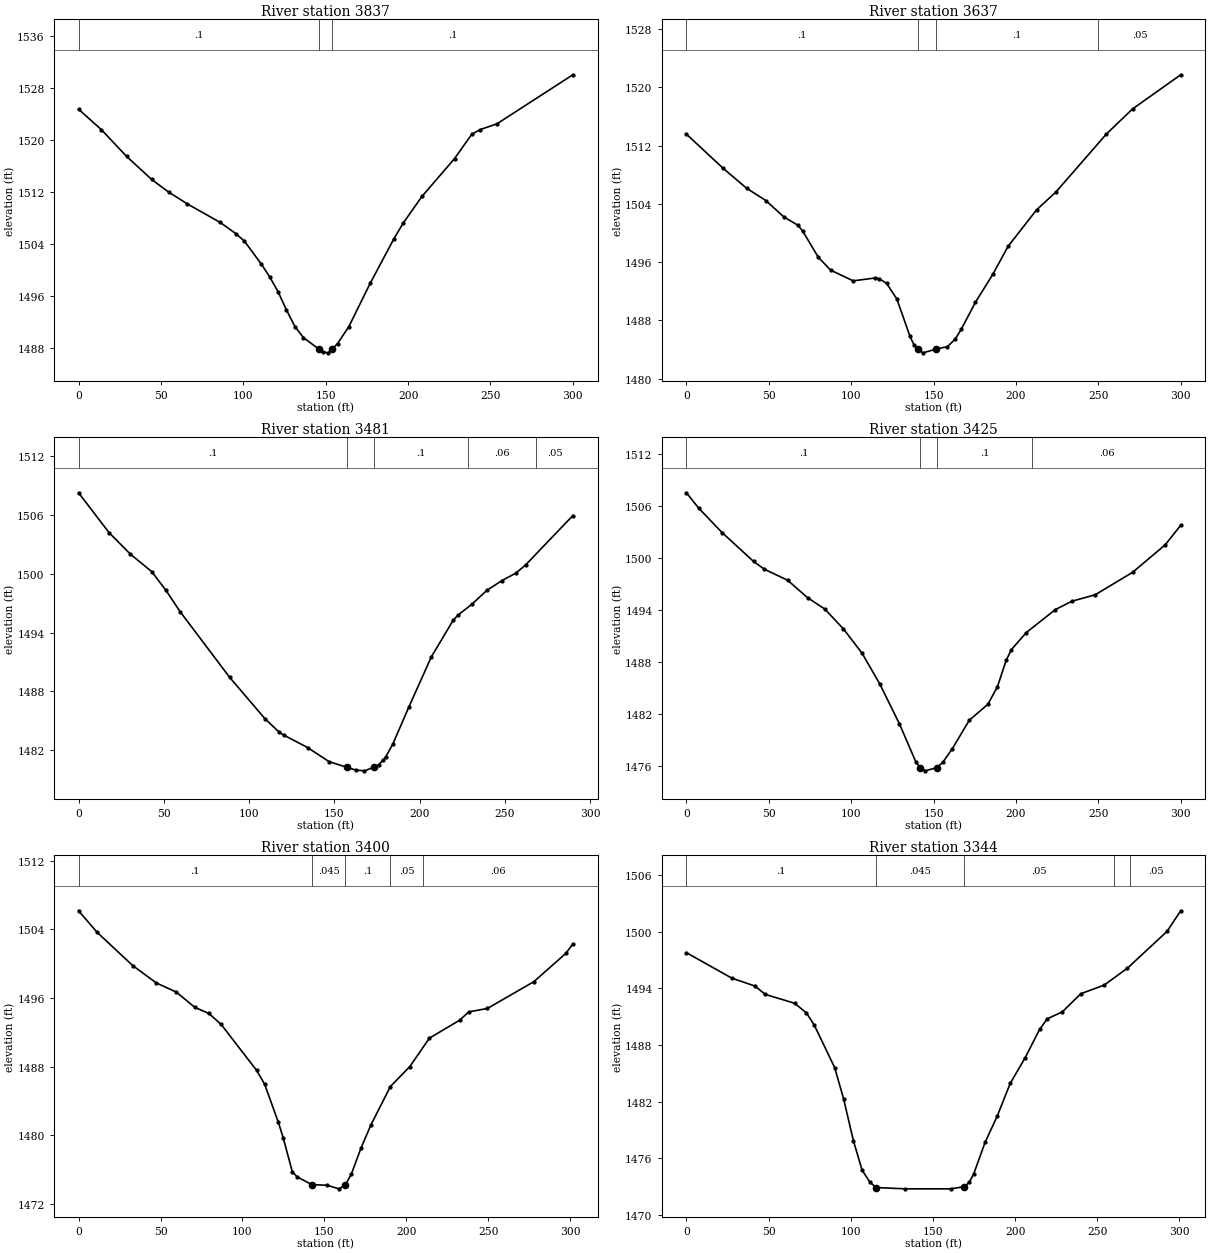
Type RM Length L Ch R = 1 ,3837    ,200,200,200
XS GIS Cut Line= 2
2191117.41161162716379.0758727312191352.13858693716565.899980015
#Sta/Elev= 30
       0  1524.7    13.8 1521.57    29.1 1517.47    44.4 1513.91    54.7 1511.97
    66.1 1510.15      86 1507.31    95.6 1505.57   100.7 1504.43   110.9 1500.93
     116 1498.96   121.1 1496.67   126.2 1493.86   131.3 1491.33   136.5 1489.63
   145.8 1487.87   148.6 1487.41   151.5 1487.29     1541487.866   157.2 1488.72
     164 1491.29   177.1 1498.01   191.3 1504.76     197  1507.2   208.4  1511.3
   228.2 1517.12   238.7 1520.86   243.8 1521.58   253.9 1522.45     300 1529.99
#Mann= 3 ,-1,0
       0      .1       0   145.8    .045       0     154      .1       0
Bank Sta=145.8,154
XS Rating Curve= 0 ,0
Exp/Cntr(USF)=0,0
Exp/Cntr=0.3,0.1

Type RM Length L Ch R = 1 ,3637    ,156.5,156.5,156.5
XS GIS Cut Line= 2
 2191003.8250919 716534.076530922191230.19496933716730.943690672
#Sta/Elev= 30
       0 1513.57    22.3 1508.88    36.5 1506.15    48.2 1504.46    59.2  1502.2
    67.7 1501.06    70.5 1500.29      80 1496.69    87.5 1494.91   101.2 1493.44
   114.4 1493.83   117.1 1493.74   121.5 1493.08   127.7 1490.96   135.7 1485.81
   138.3 1484.57   140.61484.065   143.6 1483.56  151.571484.077   158.4 1484.41
   163.2 1485.46   166.9 1486.83   175.4  1490.5     186 1494.35   195.2 1498.17
   212.5 1503.18   224.2 1505.62   254.9 1513.59   270.8 1517.04     300 1521.72
#Mann= 4 ,-1,0
       0      .1       0   140.6    .045       0  151.57      .1       0
     250     .05       0
Bank Sta=140.6,151.57
XS Rating Curve= 0 ,0
Exp/Cntr(USF)=0,0
Exp/Cntr=0.3,0.1

Type RM Length L Ch R = 1 ,3481    ,55.6,55.6,55.6
XS GIS Cut Line= 3
2190968.46851914716587.9440344112191020.12499295716769.139050248
2191097.21234618716835.100393733
#Sta/Elev= 30
       0 1508.26    17.9 1504.19    30.4    1502    42.9 1500.22    51.2 1498.32
    59.5 1496.15    88.6 1489.44   109.4  1485.2   117.7 1483.84   120.5 1483.53
   134.4 1482.27   146.9 1480.84   157.41480.259   162.6 1479.98   167.7  1479.9
   173.11480.262     176 1480.51   178.8 1481.03   180.1 1481.31   184.3 1482.62
   193.7  1486.4   206.9 1491.52   219.7 1495.25   222.5 1495.78   230.6 1496.88
   239.5 1498.31   248.1 1499.28   256.6 1500.08   262.2  1500.9   289.9 1505.93
#Mann= 5 ,-1,0
       0      .1       0   157.4    .045       0   173.1      .1       0
  228.41     .06       0  268.41     .05       0
Bank Sta=157.4,173.1
XS Rating Curve= 0 ,0
Exp/Cntr(USF)=0,0
Exp/Cntr=0.3,0.1

Type RM Length L Ch R = 1 ,3425    ,25.2,25.2,25.2
XS GIS Cut Line= 2
2190859.12823344716643.5070912072191064.20252282716862.469498556
#Sta/Elev= 30
       0 1507.49     7.6 1505.68    21.7 1502.89    40.7 1499.58    47.2 1498.68
    61.4 1497.41    73.5  1495.4      84 1494.08    95.3 1491.79   106.6 1488.99
   117.4 1485.43   129.3 1480.84   139.3 1476.43     142 1475.79   144.8 1475.43
   151.9 1475.79   155.7 1476.44   161.2 1477.93   171.7 1481.27     183 1483.11
   188.8 1485.15   194.1 1488.19   197.2  1489.4   206.3 1491.38   223.9 1494.02
     234 1494.99   248.1 1495.73   270.8 1498.32   290.6 1501.49     300 1503.74
#Mann= 4 ,-1,0
       0      .1       0     142    .045       0   151.9      .1       0
     210     .06       0
Bank Sta=142,151.9
XS Rating Curve= 0 ,0
Exp/Cntr(USF)=0,0
Exp/Cntr=0.3,0.1

Type RM Length L Ch R = 1 ,3400    ,55.5,55.5,55.5
XS GIS Cut Line= 2
2190840.30155029  716656.79029692191043.02192578716879.925136428
#Sta/Elev= 30
       0 1506.18    11.3 1503.67      33 1499.79    47.4 1497.76    59.7 1496.68
    70.8 1494.92    79.5 1494.19      87 1492.91   108.6 1487.55   113.5 1485.94
   121.9 1481.47   124.8  1479.7   130.4 1475.71   133.3 1475.12   142.31474.213
   151.8 1474.13   158.8 1473.72   162.7 1474.16   166.4 1475.44   172.3 1478.49
   178.3 1481.17   190.2 1485.66   202.1    1488     214 1491.31   232.4  1493.4
     238 1494.37   249.4 1494.78   277.7  1497.9   297.2  1501.2   301.5  1502.3
#Mann= 5 ,-1,0
       0      .1       0   142.3    .045       0   162.7      .1       0
     190     .05       0     210     .06       0
Bank Sta=142.3,162.7
XS Rating Curve= 0 ,0
Exp/Cntr(USF)=0,0
Exp/Cntr=0.3,0.1

Type RM Length L Ch R = 1 ,3344    ,53.4,53.4,53.4
XS GIS Cut Line= 2
 2190793.3008075716709.0133444492191016.43564703 716910.78420998
#Sta/Elev= 30
       0 1497.78    27.6 1495.08    41.6 1494.25      48 1493.36    65.8 1492.42
      73  1491.4    77.8  1490.1    90.2  1485.6    95.6 1482.32   101.6 1477.86
   106.9 1474.73   111.7 1473.45   115.4 1472.89   133.3 1472.75   160.7 1472.75
   169.2 1472.98   172.1 1473.44   174.9 1474.37   181.8  1477.7   189.1 1480.44
   197.1 1483.95   206.1 1486.63   214.9 1489.64   219.6 1490.77   228.7  1491.5
     240 1493.43   254.2 1494.34   268.4 1496.14   292.5 1500.04   300.8 1502.22
#Mann= 5 ,-1,0
       0      .1       0   115.4    .045       0   169.2     .05       0
     260     .06       0     270     .05       0
Bank Sta=115.4,169.2
XS Rating Curve= 0 ,0
Exp/Cntr(USF)=0,0
Exp/Cntr=0.3,0.1

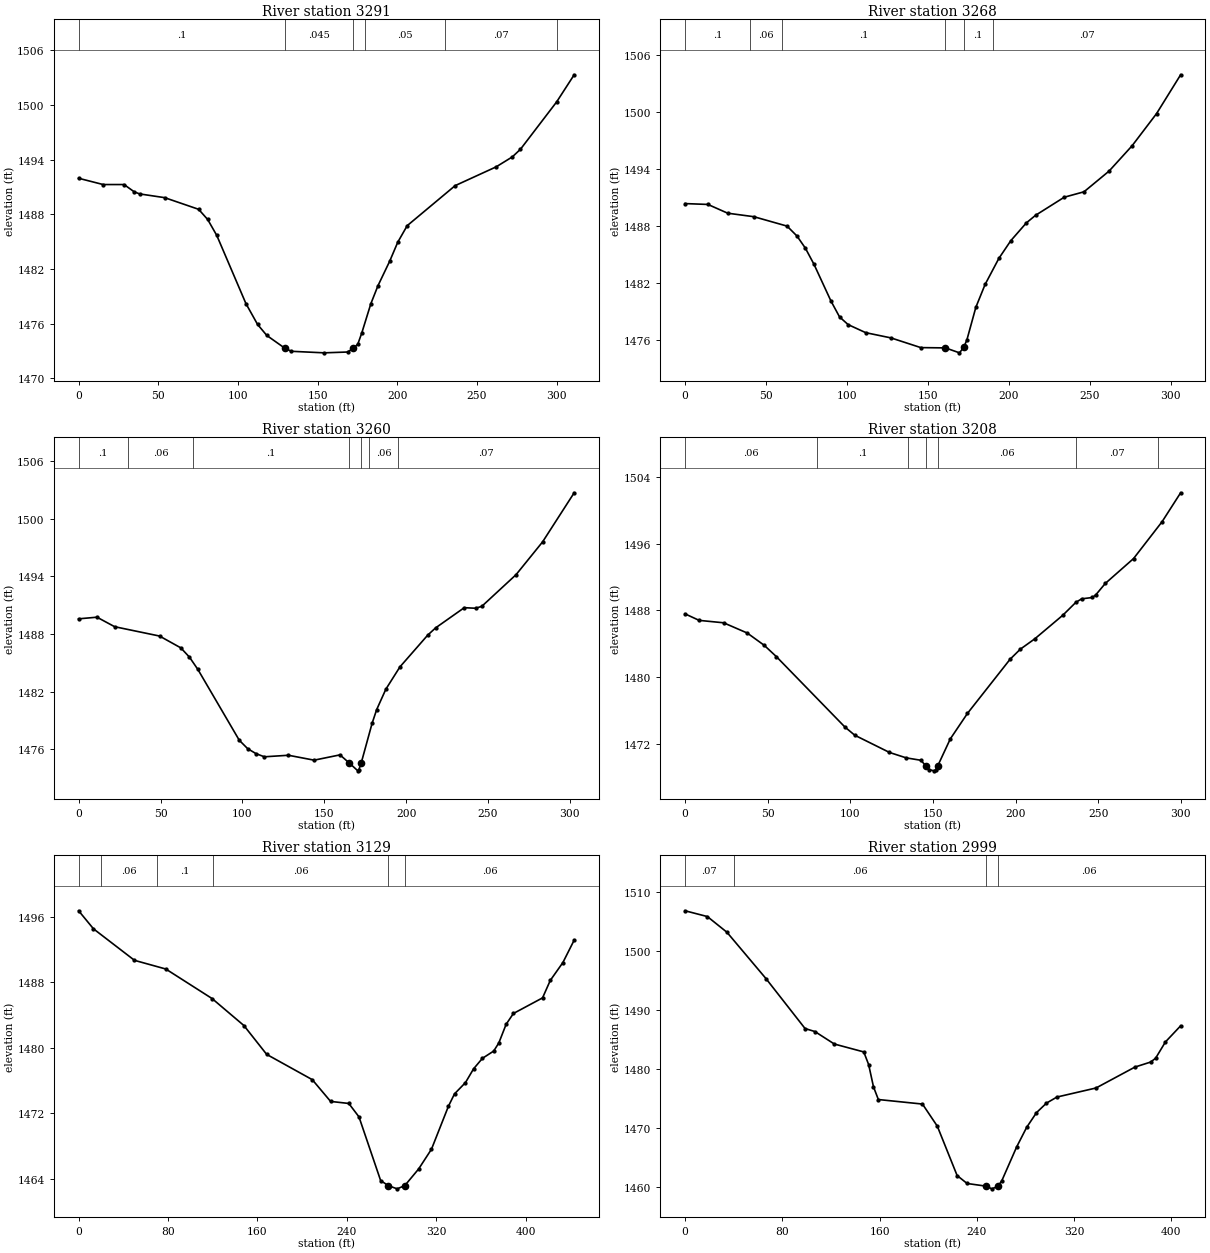
Type RM Length L Ch R = 1 ,3291    ,23.2,23.2,23.2
XS GIS Cut Line= 2
2190748.19908462716751.2665374662190990.32412325716946.390833309
#Sta/Elev= 30
       0 1491.96    15.4 1491.27    28.5 1491.27    34.9 1490.47    38.3 1490.24
      54 1489.83    75.3 1488.55      81 1487.43    86.7 1485.68     105 1478.19
   112.3  1475.9   118.1 1474.69   129.4 1473.29   133.5 1472.95   154.1 1472.78
   168.8 1472.87   172.4 1473.28   175.2 1473.73   177.7 1474.96   183.4 1478.18
   187.9 1480.17   195.2 1482.84   200.3 1484.94   206.2 1486.75   236.3 1491.15
     262 1493.21   272.2 1494.31   277.3 1495.15     300 1500.35     311 1503.33
#Mann= 6 ,-1,0
       0      .1       0   129.4    .045       0   172.4      .1       0
     180     .05       0     230     .07       0     300     .05       0
Bank Sta=129.4,172.4
XS Rating Curve= 0 ,0
Exp/Cntr(USF)=0,0
Exp/Cntr=0.3,0.1

Type RM Length L Ch R = 1 ,3268    ,7.3,7.3,7.3
XS GIS Cut Line= 2
2190744.01262379716767.9386965052190975.49033952716968.272926738
#Sta/Elev= 30
       0 1490.35    14.1 1490.26    26.3 1489.34    42.5 1488.97      63 1487.98
    69.1 1486.94    74.3 1485.66    79.6 1483.97    90.1  1480.1    95.4 1478.43
   100.7 1477.62   111.6 1476.77   127.2 1476.22   145.6  1475.2   160.8 1475.17
   169.5 1474.65  172.041475.217     174 1475.97   179.6 1479.44   185.3 1481.84
   193.8 1484.58   201.2 1486.45   210.8 1488.32   216.5 1489.12   234.2 1491.02
   246.4 1491.59   261.9 1493.77   276.1 1496.43   291.2 1499.81   306.1  1503.9
#Mann= 6 ,-1,0
       0      .1       0      40     .06       0      60      .1       0
   160.8    .045       0  172.04      .1       0     190     .07       0
Bank Sta=160.8,172.04
XS Rating Curve= 0 ,0
Exp/Cntr(USF)=0,0
Exp/Cntr=0.3,0.1

Type RM Length L Ch R = 1 ,3260    ,52.3,52.3,52.3
XS GIS Cut Line= 4
2190734.79031825716778.8036150652190859.00487378716875.706610524
2190878.42999219716895.0644520622190955.75307943716983.712095318
#Sta/Elev= 30
       0 1489.58    11.2 1489.75      22 1488.76    49.4 1487.79    62.4 1486.56
    67.7 1485.59    72.8 1484.32    98.1 1476.95   103.2 1476.08   108.3 1475.56
   113.4 1475.23   128.1 1475.39   143.8 1474.88   159.6 1475.43   165.3 1474.58
   170.5 1473.77     171 1473.83  172.53 1474.57   179.2 1478.71     182 1480.14
   187.6 1482.26   196.2 1484.58   213.2 1487.89     218 1488.64   235.5 1490.74
   242.4 1490.68   246.2 1490.88   267.1 1494.17   283.3 1497.58   302.6 1502.69
#Mann= 7 ,-1,0
       0      .1       0      30     .06       0      70      .1       0
   165.3    .045       0  172.53      .1       0  177.54     .06       0
  194.97     .07       0
Bank Sta=165.3,172.53
XS Rating Curve= 0 ,0
Exp/Cntr(USF)=0,0
Exp/Cntr=0.3,0.1

Type RM Length L Ch R = 1 ,3208    ,78.6,78.6,78.6
XS GIS Cut Line= 4
2190722.90158978716798.5435045722190796.81008309716858.147128203
2190827.80396737716922.5190417242190935.09048991717001.990539898
#Sta/Elev= 30
       0 1487.59     8.5 1486.81    23.3 1486.52    37.6 1485.29    47.9 1483.81
    55.2 1482.46    96.7 1473.99   102.7    1473   123.7 1470.93   133.8 1470.28
   142.7 1469.99   145.81469.294   147.7 1468.86   150.7 1468.72   151.6 1468.79
   152.81469.276   160.5 1472.56   170.9 1475.63   196.7 1482.14   202.9 1483.35
   211.7  1484.6   228.6 1487.43   236.5 1488.98     240  1489.4   246.5 1489.56
   248.6 1489.89   254.3 1491.25   271.4 1494.24   288.7 1498.68   299.9 1502.15
#Mann= 7 ,-1,0
       0     .06       0      80      .1       0  134.95     .06       0
   145.8    .045       0   152.8     .06       0  236.39     .07       0
  286.39     .05       0
Bank Sta=145.8,152.8
XS Rating Curve= 0 ,0
Exp/Cntr(USF)=0,0
Exp/Cntr=0.3,0.1

Type RM Length L Ch R = 1 ,3129    ,130.7,130.7,130.7
XS GIS Cut Line= 3
2190672.83454593716680.1309722932190721.31215982716921.724326742
2190877.07629624717042.521003967
#Sta/Elev= 30
       0 1496.76    13.3 1494.55      50  1490.7      78 1489.64   119.4 1486.03
   147.9 1482.73   168.3  1479.2   209.1 1476.11   225.5 1473.45   241.8  1473.2
   250.9 1471.56   270.3 1463.77   277.2 1463.15   285.1 1462.76   291.91463.157
   304.3 1465.19   315.8 1467.61     331 1472.87   336.4 1474.37   346.2 1475.75
   353.5 1477.44   361.4 1478.72   371.5 1479.61   376.1 1480.61   382.6 1482.88
   389.1  1484.2   415.2 1486.11   422.1 1488.24   433.4 1490.43   443.5 1493.17
#Mann= 6 ,-1,0
       0      .1       0      20     .06       0      70      .1       0
     120     .06       0   277.2    .045       0   291.9     .06       0
Bank Sta=277.2,291.9
XS Rating Curve= 0 ,0
Exp/Cntr(USF)=0,0
Exp/Cntr=0.3,0.1

Type RM Length L Ch R = 1 ,2999    ,65.5,65.5,65.5
XS GIS Cut Line= 3
2190450.00590468716998.6068613422190641.04594666717018.679554514
2190852.42743157 717061.29661452
#Sta/Elev= 30
       0 1506.81    18.3 1505.83    34.4 1503.17    66.5 1495.31    98.7 1486.82
   106.8 1486.31   122.8 1484.19     147 1482.85     151 1480.71     155 1476.92
     159 1474.77   195.3    1474   207.5 1470.25   223.8 1461.87     232 1460.52
   247.8 1460.06   252.4 1459.61   257.41460.039   260.6    1461   272.8 1466.73
     281 1470.04   289.1 1472.54   297.3 1474.16   305.9 1475.19   338.1 1476.73
   370.1 1480.28     383 1481.13   387.1 1481.78   395.2 1484.55   407.7 1487.28
#Mann= 4 ,-1,0
       0     .07       0      40     .06       0   247.8    .045       0
   257.4     .06       0
Bank Sta=247.8,257.4
XS Rating Curve= 0 ,0
Exp/Cntr(USF)=0,0
Exp/Cntr=0.3,0.1

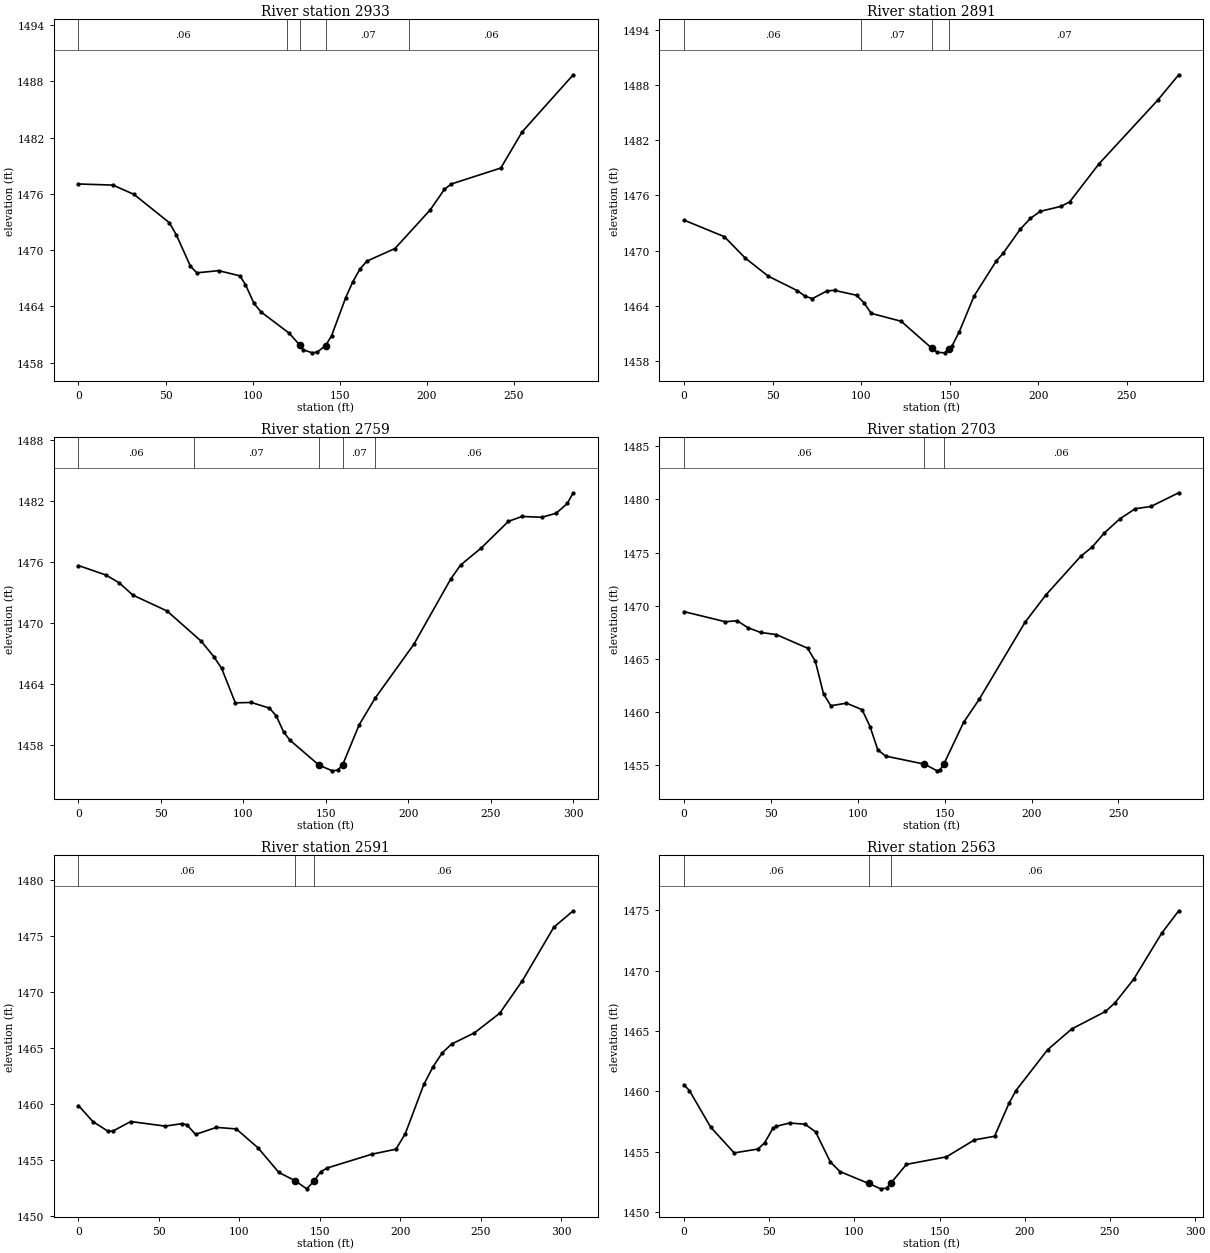
Type RM Length L Ch R = 1 ,2933    ,42.8,42.8,42.8
XS GIS Cut Line= 2
2190576.67403314717115.634782287 2190857.2084217717070.336028327
#Sta/Elev= 30
       0 1477.06    19.8 1476.94    31.9 1475.95    52.2 1472.93    56.2 1471.64
    64.3  1468.3      68 1467.59    80.5 1467.82    92.7 1467.27    95.9 1466.34
   100.8 1464.34   104.8 1463.43     121 1461.16   127.31459.848   129.2 1459.38
   134.3 1459.06   137.3 1459.16     142 1459.84   145.4 1460.89   153.5 1464.94
   157.5  1466.6   161.6 1467.96   165.6 1468.83   181.8 1470.18   202.1 1474.31
   210.2 1476.49   214.2 1477.06   242.6 1478.76   254.8  1482.6   284.2  1488.7
#Mann= 5 ,-1,0
       0     .06       0     120     .07       0   127.3    .045       0
     142     .07       0     190     .06       0
Bank Sta=127.3,142
XS Rating Curve= 0 ,0
Exp/Cntr(USF)=0,0
Exp/Cntr=0.3,0.1

Type RM Length L Ch R = 1 ,2891    ,131.1,131.1,131.1
XS GIS Cut Line= 2
2190590.18418783717169.6754010452190859.59256664717096.561622725
#Sta/Elev= 30
       0 1473.32    22.8 1471.52    34.6 1469.19    47.6 1467.22      64 1465.65
    68.4 1465.04    72.5 1464.79    80.8 1465.63      85 1465.68    97.4 1465.15
   101.5 1464.35   105.7 1463.18   122.6 1462.32     1401459.364     143 1458.95
   147.1 1458.89   149.61459.343   151.3 1459.65   155.4  1461.2   163.7 1465.06
   176.1 1468.84   180.3 1469.76   189.8 1472.34   195.5 1473.51     201 1474.27
   212.6 1474.81   217.6 1475.29   234.2 1479.44   267.3 1486.35   279.2 1489.12
#Mann= 4 ,-1,0
       0     .06       0     100     .07       0     140    .045       0
   149.6     .07       0
Bank Sta=140,149.6
XS Rating Curve= 0 ,0
Exp/Cntr(USF)=0,0
Exp/Cntr=0.3,0.1

Type RM Length L Ch R = 1 ,2759    ,56.6,56.6,56.6
XS GIS Cut Line= 2
2190620.31539884717293.6720304112190910.15179827717216.245539029
#Sta/Elev= 30
       0 1475.66    16.6 1474.73    24.7 1473.96      33 1472.75    53.7 1471.19
    74.4 1468.22      82 1466.71    86.8 1465.55    95.1 1462.15   104.8 1462.19
   115.8 1461.63   119.9 1460.87   124.4 1459.29   128.2 1458.48   145.81456.027
   153.9 1455.46   157.1 1455.53   160.11456.021   170.2 1459.99     180 1462.64
   203.4 1467.92   225.7 1474.33   231.7 1475.71   244.1 1477.37   260.7 1480.01
     269 1480.49   280.9 1480.41   289.7 1480.81   296.4 1481.77     300 1482.82
#Mann= 5 ,-1,0
       0     .06       0      70     .07       0   145.8    .045       0
   160.1     .07       0     180     .06       0
Bank Sta=145.8,160.1
XS Rating Curve= 0 ,0
Exp/Cntr(USF)=0,0
Exp/Cntr=0.3,0.1

Type RM Length L Ch R = 1 ,2703    ,111.3,111.3,111.3
XS GIS Cut Line= 2
2190664.88739612717369.9435764432190918.40147529 717240.40503442
#Sta/Elev= 30
       0 1469.44    23.8 1468.49    30.6 1468.58    36.8 1467.93    44.1 1467.48
    53.1 1467.28    71.1    1466    75.6 1464.77    80.3  1461.7    84.5 1460.58
    93.5 1460.82   102.5 1460.21   107.1 1458.61   111.5 1456.44     116 1455.84
   138.4 1455.08   145.7 1454.45   147.4 1454.57   149.51455.077   160.9 1459.01
   169.9 1461.19   196.2 1468.42   208.1 1470.98   228.3 1474.65   234.9 1475.52
   241.8 1476.83   250.7 1478.16   259.7 1479.13   268.7 1479.34   284.7 1480.63
#Mann= 3 ,-1,0
       0     .06       0   138.4    .045       0   149.5     .06       0
Bank Sta=138.4,149.5
XS Rating Curve= 0 ,0
Exp/Cntr(USF)=0,0
Exp/Cntr=0.3,0.1

Type RM Length L Ch R = 1 ,2591    ,28.1,28.1,28.1
XS GIS Cut Line= 3
2190700.64957029717457.3622244352190854.02956177717395.374455859
2190952.57421951717292.856223215
#Sta/Elev= 30
       0 1459.86       9 1458.42    18.2 1457.58    21.3 1457.57    32.5 1458.43
    53.9 1458.02    64.3 1458.24    67.4 1458.14    72.8 1457.28    85.8 1457.91
    98.1 1457.77   111.7 1456.07   124.6 1453.88   134.71453.144   141.9 1452.42
   146.71453.153   150.5 1453.94   154.8 1454.29   182.6 1455.52   197.4 1455.96
   203.2 1457.35   214.7 1461.74   220.5 1463.34   226.2 1464.57     232 1465.35
   246.2 1466.35   261.9  1468.1     276 1471.01   295.5 1475.78   307.6 1477.25
#Mann= 3 ,-1,0
       0     .06       0   134.7    .045       0   146.7     .06       0
Bank Sta=134.7,146.7
XS Rating Curve= 0 ,0
Exp/Cntr(USF)=0,0
Exp/Cntr=0.3,0.1

Type RM Length L Ch R = 1 ,2563    ,32.7,32.7,32.7
XS GIS Cut Line= 3
2190745.55096676717502.2636209032190827.40660988717444.249427236
2190957.73986689717305.969020413
#Sta/Elev= 30
       0 1460.54     3.2 1460.06    15.7 1457.02    29.5 1454.89    43.4 1455.21
    47.3 1455.72    52.2 1456.93    54.3  1457.1      62 1457.37    71.1 1457.27
    77.3 1456.63    85.9 1454.14    91.6 1453.34   108.41452.357   115.5 1451.91
   118.9 1451.97   121.31452.359   130.6 1453.94     154 1454.56   170.5 1455.97
   182.3 1456.27   190.8 1459.01   194.8 1460.05   213.4 1463.44   227.6 1465.17
   247.4 1466.62     253 1467.34     264  1469.3   280.4 1473.11   290.4 1474.97
#Mann= 3 ,-1,0
       0     .06       0   108.4    .045       0   121.3     .06       0
Bank Sta=108.4,121.3
XS Rating Curve= 0 ,0
Exp/Cntr(USF)=0,0
Exp/Cntr=0.3,0.1

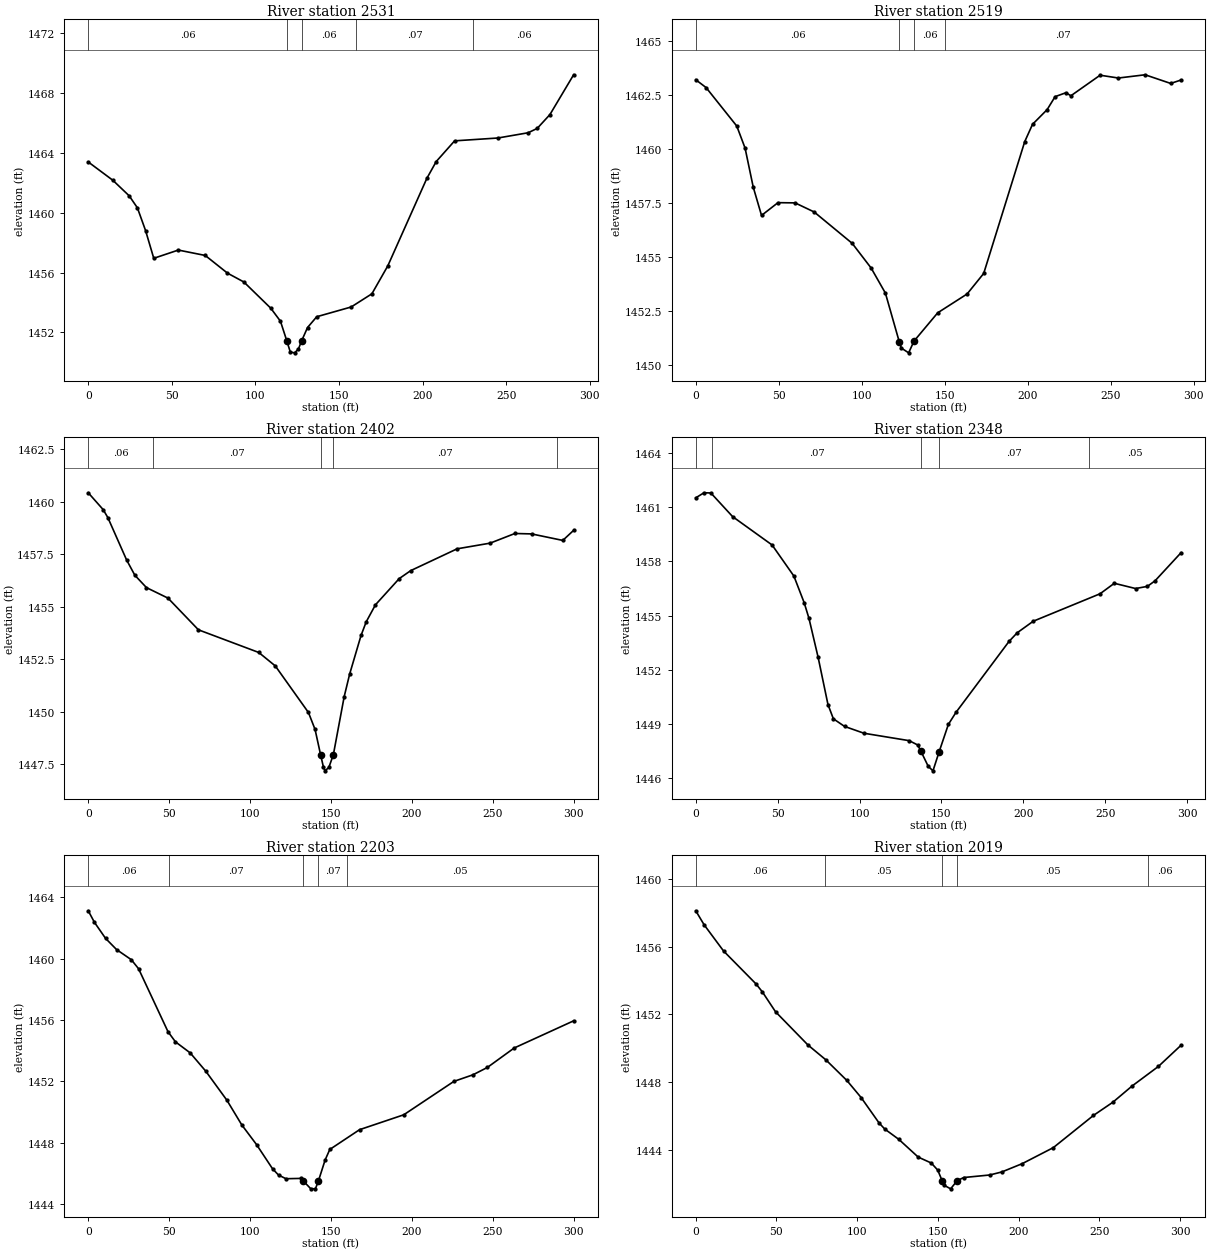
Type RM Length L Ch R = 1 ,2531    ,11.5,11.5,11.5
XS GIS Cut Line= 3
2190764.22676883717529.6812877732190846.08241195717471.667094106
2190976.41566896717333.386687284
#Sta/Elev= 30
       0 1463.38    14.7 1462.16    24.5 1461.12    29.4 1460.32    34.3  1458.8
    39.2 1456.95    53.9  1457.5      70 1457.14    83.3 1455.96    93.1 1455.37
   109.2 1453.62     115 1452.75   118.81451.438   120.9 1450.69   123.4 1450.64
   125.7 1450.88   127.61451.424   131.2 1452.33   136.7 1453.05   157.3  1453.7
   169.7 1454.58   179.2 1456.44   202.6 1462.29   208.2 1463.41   219.2 1464.79
   245.1 1464.98   263.2 1465.33   268.6 1465.62   276.2 1466.54   290.4  1469.2
#Mann= 5 ,-1,0
       0     .06       0   118.8    .045       0   127.6     .06       0
  160.33     .07       0  230.33     .06       0
Bank Sta=118.8,127.6
XS Rating Curve= 0 ,0
Exp/Cntr(USF)=0,0
Exp/Cntr=0.3,0.1

Type RM Length L Ch R = 1 ,2519    ,117.2,117.2,117.2
XS GIS Cut Line= 2
2190768.20034374717536.8337226092191004.23069332717364.380571571
#Sta/Elev= 30
       0 1463.19     6.2 1462.83    24.7 1461.05    29.7 1460.03    34.6 1458.23
    39.6 1456.92    49.5 1457.51    59.8  1457.5    71.3 1457.08    94.2 1455.63
   105.6 1454.49   114.2 1453.33   122.51451.093   123.8 1450.79   128.2 1450.57
   131.4 1451.11   145.7 1452.42   163.4 1453.29   173.4 1454.24   198.1 1460.33
   202.8 1461.13   211.6 1461.81   216.4 1462.41   222.9 1462.59   225.9 1462.45
   243.5  1463.4   254.5 1463.27   270.6 1463.42     286 1463.02   292.3 1463.18
#Mann= 4 ,-1,0
       0     .06       0   122.5    .045       0   131.4     .06       0
     150     .07       0
Bank Sta=122.5,131.4
XS Rating Curve= 0 ,0
Exp/Cntr(USF)=0,0
Exp/Cntr=0.3,0.1

Type RM Length L Ch R = 1 ,2402    ,54,54,54
XS GIS Cut Line= 2
 2190857.5966626 717607.535275982191092.58389951717421.038631268
#Sta/Elev= 30
       0 1460.43     9.2 1459.63    12.1 1459.25    23.7 1457.23    28.8  1456.5
      36 1455.91    49.3 1455.41    68.1  1453.9   105.4 1452.82   115.6 1452.18
   136.1 1449.96   140.2 1449.15   143.61447.949   145.3 1447.38   146.3 1447.18
   148.7 1447.34   151.5 1447.95   158.2 1450.72   161.6  1451.8   168.6 1453.63
   171.8 1454.28   177.5 1455.09   192.2 1456.34   199.3 1456.72     228 1457.76
   248.4 1458.03   263.7 1458.49     274 1458.47   293.3 1458.16     300 1458.64
#Mann= 5 ,-1,0
       0     .06       0      40     .07       0   143.6    .045       0
   151.5     .07       0     290     .06       0
Bank Sta=143.6,151.5
XS Rating Curve= 0 ,0
Exp/Cntr(USF)=0,0
Exp/Cntr=0.3,0.1

Type RM Length L Ch R = 1 ,2348    ,145.3,145.3,145.3
XS GIS Cut Line= 2
2190876.28158126717636.1730953262191129.79566043717482.793103851
#Sta/Elev= 30
       0 1461.52       5  1461.8     9.2 1461.79    22.5 1460.48    46.6 1458.91
    59.9 1457.19    66.2 1455.71    69.1 1454.85    74.7 1452.69    80.7 1450.08
      84 1449.29    90.8 1448.87   102.7 1448.49   130.3 1448.08   135.5 1447.84
   137.51447.485   141.9 1446.66   144.8 1446.41   148.61447.475   154.2 1448.98
   158.8 1449.64   191.2 1453.57   196.2 1454.05     206 1454.69   246.8 1456.21
   255.5 1456.79   268.5  1456.5   275.7 1456.62   280.4 1456.93   296.3 1458.49
#Mann= 5 ,-1,0
       0     .06       0      10     .07       0   137.5    .045       0
   148.6     .07       0     240     .05       0
Bank Sta=137.5,148.6
XS Rating Curve= 0 ,0
Exp/Cntr(USF)=0,0
Exp/Cntr=0.3,0.1

Type RM Length L Ch R = 1 ,2203    ,183.8,183.8,183.8
XS GIS Cut Line= 2
2190944.83302904717756.3573141312191208.42588669717613.113447254
#Sta/Elev= 30
       0 1463.12     3.8 1462.37    10.7 1461.32    17.5 1460.59    26.6 1459.93
    31.1 1459.34    49.3 1455.23    53.9 1454.57      63 1453.85    72.6 1452.66
    85.7 1450.76    94.9 1449.15     104 1447.87   113.9 1446.29   117.6 1445.88
   122.2 1445.64   131.3 1445.66     1331445.485   137.5 1444.99   140.4 1444.98
   142.21445.473   146.4 1446.86   149.3 1447.55   167.7 1448.84     195 1449.81
     226 1451.99   237.8 1452.42   246.7  1452.9   263.3 1454.17     300 1455.94
#Mann= 5 ,-1,0
       0     .06       0      50     .07       0     133    .045       0
   142.2     .07       0     160     .05       0
Bank Sta=133,142.2
XS Rating Curve= 0 ,0
Exp/Cntr(USF)=0,0
Exp/Cntr=0.3,0.1

Type RM Length L Ch R = 1 ,2019    ,97.6,97.6,97.6
XS GIS Cut Line= 2
2191003.07308554717844.5112695612191302.25302484717813.840182527
#Sta/Elev= 30
       0 1458.14     5.1 1457.32    17.2 1455.76    37.3 1453.81    41.3 1453.33
    49.4 1452.16    69.5 1450.19    80.6 1449.31    93.6 1448.09   102.5 1447.07
   113.5 1445.58   117.1 1445.21   125.8  1444.6   137.8 1443.55   145.9  1443.2
   149.9 1442.78   152.71442.135   153.9 1441.88   157.9 1441.67   161.9 1442.15
     166 1442.34   182.1 1442.49   189.6 1442.67   202.2 1443.16   221.5 1444.11
   246.4 1446.02   258.4  1446.8   270.3 1447.76   286.6 1448.92   300.7 1450.18
#Mann= 5 ,-1,0
       0     .06       0      80     .05       0   152.7    .045       0
   161.9     .05       0     280     .06       0
Bank Sta=152.7,161.9
XS Rating Curve= 0 ,0
Exp/Cntr(USF)=0,0
Exp/Cntr=0.3,0.1