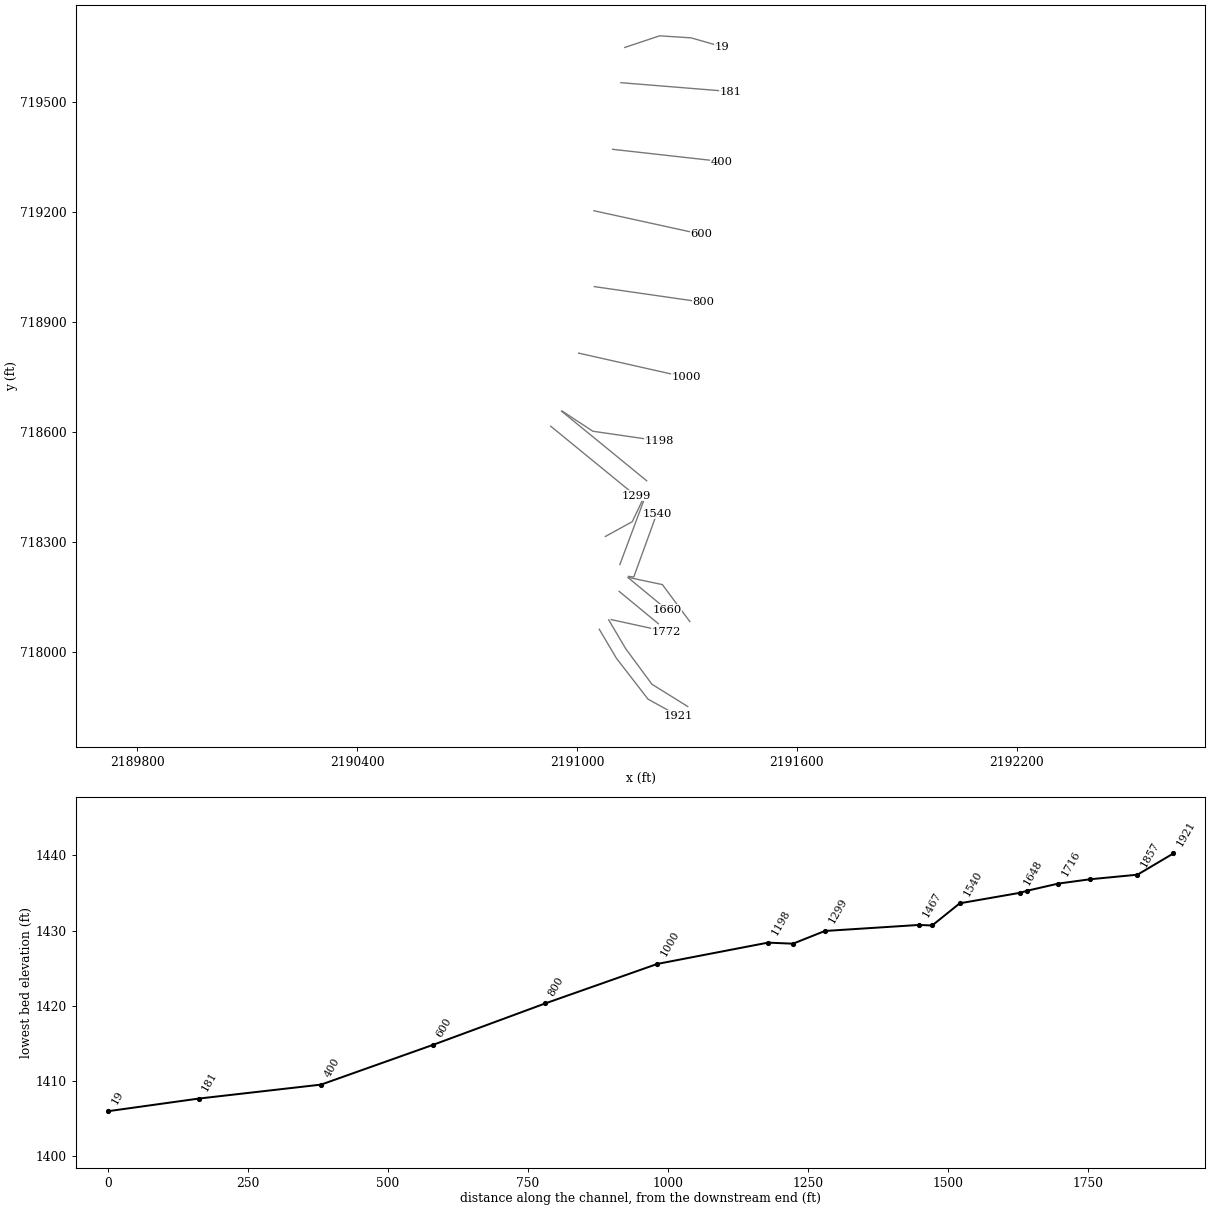
HEC-RAS study LISANDRNTR.prj: LISANDRNTR

--- LISANDRNTR.g01 (geometry) --- (continued)

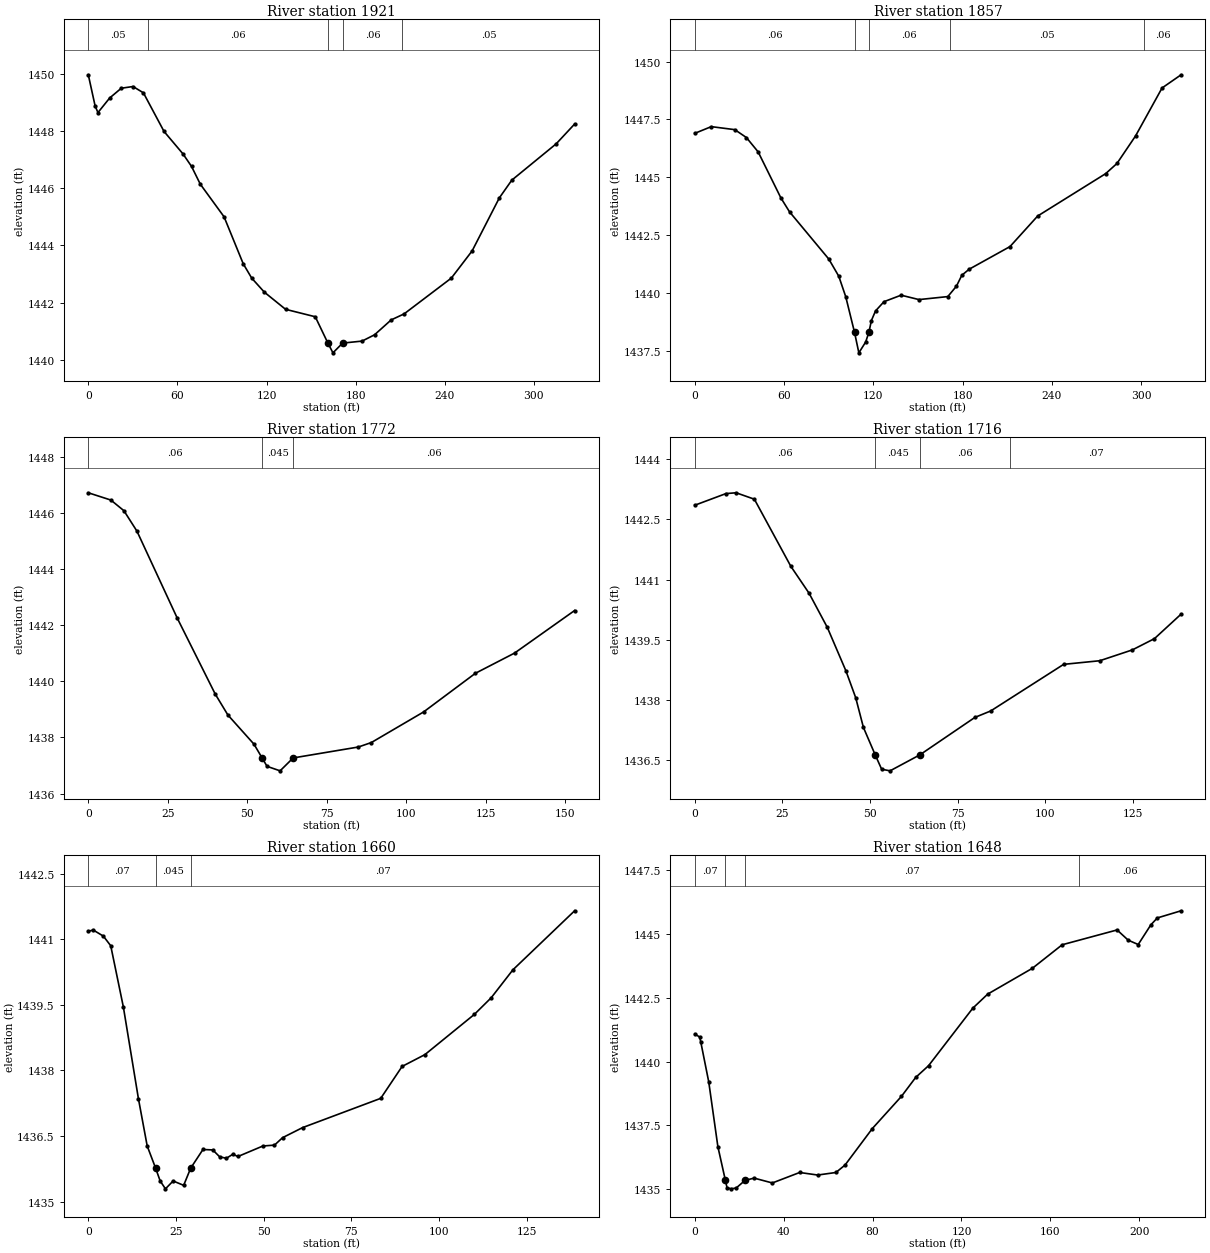
Type RM Length L Ch R = 1 ,1921    ,64.2,64.2,64.2
XS GIS Cut Line= 4
 2191060.8784796718061.1266907432191107.34429808717982.426587337
2191193.96823109717870.3717749112191276.59490948717824.739465812
#Sta/Elev= 30
       0 1449.96     4.6 1448.87     6.5 1448.64    14.4 1449.15    22.2 1449.49
    30.1 1449.55    37.1 1449.33      51 1447.98    63.7  1447.2    69.5 1446.76
    75.4 1446.14    91.4    1445   104.3 1443.36     110 1442.86   118.5 1442.37
   132.8 1441.77   152.8 1441.51   161.3 1440.59   164.7 1440.25   171.2 1440.59
   184.3 1440.66   192.7 1440.88   203.9  1441.4   212.6 1441.61   244.4 1442.86
   258.4 1443.81   276.7 1445.66   285.1 1446.28     315 1447.55   327.4 1448.24
#Mann= 5 ,-1,0
       0     .05       0      40     .06       0   161.3    .045       0
   171.2     .06       0  211.39     .05       0
Bank Sta=161.3,171.2
XS Rating Curve= 0 ,0
Exp/Cntr(USF)=0,0
Exp/Cntr=0.3,0.1

Type RM Length L Ch R = 1 ,1857    ,85,85,85
XS GIS Cut Line= 4
2191086.50870188718086.7998101872191132.97452036 718008.09970678
2191204.49886872717911.1444790082191302.22513176717850.412585256
#Sta/Elev= 30
       0  1446.9    11.1 1447.19    26.9 1447.06    34.7 1446.72    42.6  1446.1
    57.9 1444.11    63.7 1443.51    90.1 1441.47    96.8 1440.73   101.5 1439.84
   107.41438.302   110.3 1437.42   114.9 1437.89   117.1 1438.32   118.7 1438.81
   121.5 1439.23   127.2 1439.63   138.7 1439.91   150.7 1439.72   170.1 1439.85
   175.9  1440.3   179.5 1440.77   184.4 1441.03   211.9 1442.01   230.5 1443.33
   276.2 1445.16   283.8  1445.6   296.3 1446.79   314.1 1448.86   326.9 1449.43
#Mann= 5 ,-1,0
       0     .06       0   107.4    .045       0   117.1     .06       0
  171.39     .05       0  301.88     .06       0
Bank Sta=107.4,117.1
XS Rating Curve= 0 ,0
Exp/Cntr(USF)=0,0
Exp/Cntr=0.3,0.1

Type RM Length L Ch R = 1 ,1772    ,56.2,56.2,56.2
XS GIS Cut Line= 2
2191093.23877127718087.5712049542191242.64518784718054.987890703
#Sta/Elev= 18
       0 1446.73     7.1 1446.47    11.2 1446.09    15.3 1445.36      28 1442.25
    39.9 1439.55    43.9  1438.8    52.1 1437.76    54.61437.278    56.2 1436.97
    60.3 1436.81    64.4 1437.27    84.9 1437.66      89 1437.82   105.4 1438.91
   121.7 1440.29     134 1441.01   152.9 1442.53
#Mann= 3 ,-1,0
       0     .06       0    54.6    .045       0    64.4     .06       0
Bank Sta=54.6,64.4
XS Rating Curve= 0 ,0
Exp/Cntr(USF)=0,0
Exp/Cntr=0.3,0.1

Type RM Length L Ch R = 1 ,1716    ,55.6,55.6,55.6
XS GIS Cut Line= 2
2191115.04704617718164.5965383332191222.04089107718076.373543414
#Sta/Elev= 21
       0 1442.85     8.9 1443.14    11.8 1443.16      17    1443    27.4 1441.33
    32.6 1440.66    37.8 1439.81    43.1 1438.73    45.9 1438.06    48.1 1437.32
    51.5 1436.63    53.3 1436.28    55.7 1436.24    64.21436.638    79.9 1437.57
    84.4 1437.73   105.2 1438.89   115.5 1438.98   124.8 1439.25   131.1 1439.53
   138.7 1440.14
#Mann= 4 ,-1,0
       0     .06       0    51.5    .045       0    64.2     .06       0
      90     .07       0
Bank Sta=51.5,64.2
XS Rating Curve= 0 ,0
Exp/Cntr(USF)=0,0
Exp/Cntr=0.3,0.1

Type RM Length L Ch R = 1 ,1660    ,12.3,12.3,12.3
XS GIS Cut Line= 2
2191139.20883511 718202.250052342191246.20268001718114.027057422
#Sta/Elev= 30
       0 1441.18     1.4 1441.21     4.3 1441.07     6.4 1440.85      10 1439.45
    14.3 1437.35    16.8 1436.27    19.21435.763    20.5 1435.47      22 1435.29
    24.2 1435.47    27.2 1435.37    29.21435.763    32.7 1436.19    35.5 1436.18
    37.5 1436.02    39.4 1435.99    41.2 1436.08    42.7 1436.03    49.8 1436.27
    53.1 1436.29    55.4 1436.46    61.1 1436.69    83.4 1437.36    89.5 1438.09
      96 1438.36   110.1 1439.28   114.9 1439.66   121.1  1440.3   138.7 1441.65
#Mann= 3 ,-1,0
       0     .07       0    19.2    .045       0    29.2     .07       0
Bank Sta=19.2,29.2
XS Rating Curve= 0 ,0
Exp/Cntr(USF)=0,0
Exp/Cntr=0.3,0.1

Type RM Length L Ch R = 1 ,1648    ,108,108,108
XS GIS Cut Line= 3
 2191142.0244626 718202.250052342191233.06308502718183.009931108
2191308.02268858718082.097831895
#Sta/Elev= 30
       0 1441.08     2.2 1440.96     2.7 1440.77     6.3  1439.2    10.4 1436.67
    13.71435.382    14.5 1435.07    16.2 1435.02    18.6 1435.05    22.6 1435.35
    26.7 1435.44    34.9 1435.25    47.2 1435.66    55.3 1435.56    63.5 1435.66
    67.6 1435.95    79.9 1437.38      93 1438.64    99.4 1439.38   105.2 1439.84
   125.1 1442.09   131.8 1442.64   151.9 1443.65   165.3 1444.57     190 1445.15
     195 1444.75   199.5 1444.58   205.2 1445.35   208.1 1445.62   218.8  1445.9
#Mann= 4 ,-1,0
       0     .07       0    13.7    .045       0    22.6     .07       0
  173.05     .06       0
Bank Sta=13.7,22.6
XS Rating Curve= 0 ,0
Exp/Cntr(USF)=0,0
Exp/Cntr=0.3,0.1

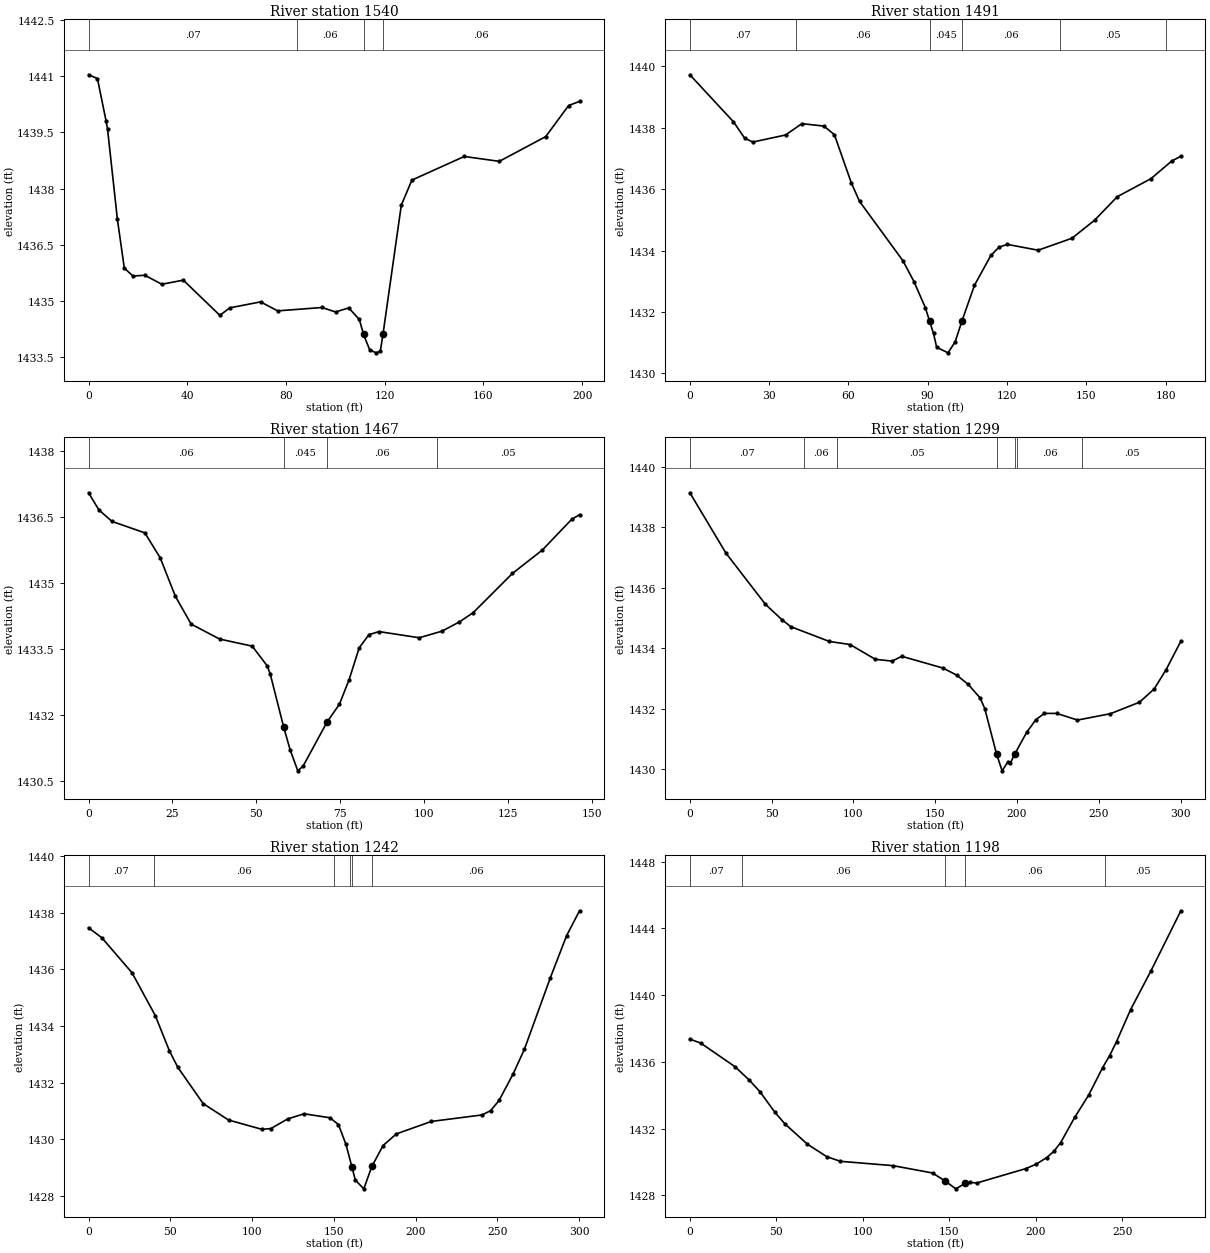
Type RM Length L Ch R = 1 ,1540    ,49.3,49.3,49.3
XS GIS Cut Line= 3
2191140.56525247718205.467394665 2191154.9936652718203.739003088
2191217.89651081 718377.02904342
#Sta/Elev= 30
       0 1441.04     3.6 1440.94     7.1 1439.81     7.7 1439.59    11.7 1437.18
    14.5 1435.88      18 1435.67    22.8 1435.69    29.7 1435.45    38.4 1435.56
    53.2 1434.62    57.2 1434.82    69.7 1434.98    76.6 1434.74    94.6 1434.83
   100.1 1434.71   105.4 1434.82   109.7 1434.51   111.41434.113   113.9  1433.7
   116.5 1433.62   118.2 1433.66   119.31434.123   126.7 1437.56     131 1438.23
   152.2 1438.86   166.4 1438.73   185.2 1439.39   194.5 1440.22   198.9 1440.33
#Mann= 4 ,-1,0
       0     .07       0   84.53     .06       0   111.4    .045       0
   119.3     .06       0
Bank Sta=111.4,119.3
XS Rating Curve= 0 ,0
Exp/Cntr(USF)=0,0
Exp/Cntr=0.3,0.1

Type RM Length L Ch R = 1 ,1491    ,23.9,23.9,23.9
XS GIS Cut Line= 2
2191117.00869638718237.7167064552191182.11841575718411.763472133
#Sta/Elev= 30
       0 1439.72    16.5 1438.19    20.7 1437.66    23.8 1437.53    36.2 1437.76
    42.4 1438.13    50.7 1438.05    54.7 1437.77    61.1  1436.2    64.2  1435.6
    80.6 1433.67    84.8 1432.99    89.1 1432.14    90.71431.707    92.2  1431.3
    93.4 1430.85    97.7 1430.67   100.4 1431.03     1031431.716   107.7 1432.87
   113.9 1433.84     117 1434.11   120.1  1434.2   131.8 1434.01   144.6  1434.4
   153.2 1434.99   161.7 1435.75   174.5 1436.34   182.3 1436.91   185.8 1437.07
#Mann= 6 ,-1,0
       0     .07       0      40     .06       0    90.7    .045       0
     103     .06       0     140     .05       0     180     .06       0
Bank Sta=90.7,103
XS Rating Curve= 0 ,0
Exp/Cntr(USF)=0,0
Exp/Cntr=0.3,0.1

Type RM Length L Ch R = 1 ,1467    ,167.5,167.5,167.5
XS GIS Cut Line= 3
2191077.45156319718314.3282472422191150.90090579718354.706158097
2191177.81951303718411.235233294
#Sta/Elev= 29
       0 1437.05     3.1 1436.66       7  1436.4    16.8 1436.14    21.4 1435.57
    25.9  1434.7    30.6 1434.07    39.1 1433.73    48.8 1433.57    53.3 1433.12
    54.2 1432.93    58.2 1431.73    60.1 1431.22    62.4 1430.74      64 1430.85
    71.11431.845    74.8 1432.25    77.7 1432.81    80.7 1433.53    83.6 1433.83
    86.6  1433.9    98.6 1433.76   105.4 1433.91   110.6 1434.12   114.7 1434.33
   126.4 1435.22   135.3 1435.75   144.1 1436.45   146.4 1436.55
#Mann= 4 ,-1,0
       0     .06       0    58.2    .045       0    71.1     .06       0
  103.82     .05       0
Bank Sta=58.2,71.1
XS Rating Curve= 0 ,0
Exp/Cntr(USF)=0,0
Exp/Cntr=0.3,0.1

Type RM Length L Ch R = 1 ,1299    ,57,57,57
XS GIS Cut Line= 2
2190928.39899106718615.1576038922191160.82086433718425.143222062
#Sta/Elev= 30
       0 1439.14    22.1 1437.14    46.2 1435.45    56.5 1434.93    61.7 1434.71
    85.3 1434.22    97.9 1434.12   113.4 1433.63   123.7 1433.57   129.5 1433.73
   154.8 1433.34   163.3  1433.1   170.2  1432.8   177.5 1432.35   180.3    1432
   187.51430.499   190.9 1429.94   194.5 1430.24     196  1430.2   198.71430.505
   205.9 1431.21   211.5 1431.63   216.7 1431.84   224.3 1431.84     237 1431.62
   257.1 1431.83   274.9 1432.21   283.9 1432.65   291.2 1433.29   300.2 1434.23
#Mann= 7 ,-1,0
       0     .07       0      70     .06       0      90     .05       0
   187.5    .045       0   198.7     .05       0     200     .06       0
     240     .05       0
Bank Sta=187.5,198.7
XS Rating Curve= 0 ,0
Exp/Cntr(USF)=0,0
Exp/Cntr=0.3,0.1

Type RM Length L Ch R = 1 ,1242    ,44.6,44.6,44.6
XS GIS Cut Line= 2
2190957.87354941 718656.320937992191190.29542268 718466.30655616
#Sta/Elev= 30
       0 1437.47     8.1 1437.12    26.6 1435.88    40.8 1434.37    49.4 1433.13
    54.6 1432.54    70.1 1431.26    85.6 1430.68   106.1 1430.35   111.5 1430.38
   121.8 1430.72   131.8  1430.9   147.6 1430.76   152.8 1430.52   157.4 1429.82
     1611429.033   163.1 1428.56   168.3 1428.25   173.21429.039   180.1 1429.78
   188.2 1430.19   209.6 1430.63   240.6 1430.86   245.8 1431.01     251 1431.37
   259.7 1432.32   266.5 1433.18   282.4 1435.71   292.3 1437.19   300.2 1438.07
#Mann= 6 ,-1,0
       0     .07       0      40     .06       0     150     .05       0
     160     .06       0     161    .045       0   173.2     .06       0
Bank Sta=161,173.2
XS Rating Curve= 0 ,0
Exp/Cntr(USF)=0,0
Exp/Cntr=0.3,0.1

Type RM Length L Ch R = 1 ,1198    ,197.5,197.5,197.5
XS GIS Cut Line= 3
2190959.43891097718656.6277769412191043.25367864718601.532754835
2191224.95002814718575.157478296
#Sta/Elev= 30
       0 1437.36     6.3 1437.12    26.1 1435.71    34.4  1434.9    40.6  1434.2
    49.2 1432.97      55 1432.28    67.9 1431.07    79.1 1430.32      87 1430.04
   117.4 1429.78   140.3 1429.34   147.51428.868   153.8 1428.39   159.21428.719
   161.9 1428.78   165.9 1428.74   194.2  1429.6   200.3 1429.87   206.3 1430.26
   210.4 1430.63   214.4 1431.16   222.5 1432.67   230.6 1434.01   238.7 1435.66
   242.7 1436.37   246.7 1437.21   254.8 1439.12   266.5 1441.43   283.9 1445.05
#Mann= 5 ,-1,0
       0     .07       0      30     .06       0   147.5    .045       0
   159.2     .06       0   240.3     .05       0
Bank Sta=147.5,159.2
XS Rating Curve= 0 ,0
Exp/Cntr(USF)=0,0
Exp/Cntr=0.3,0.1

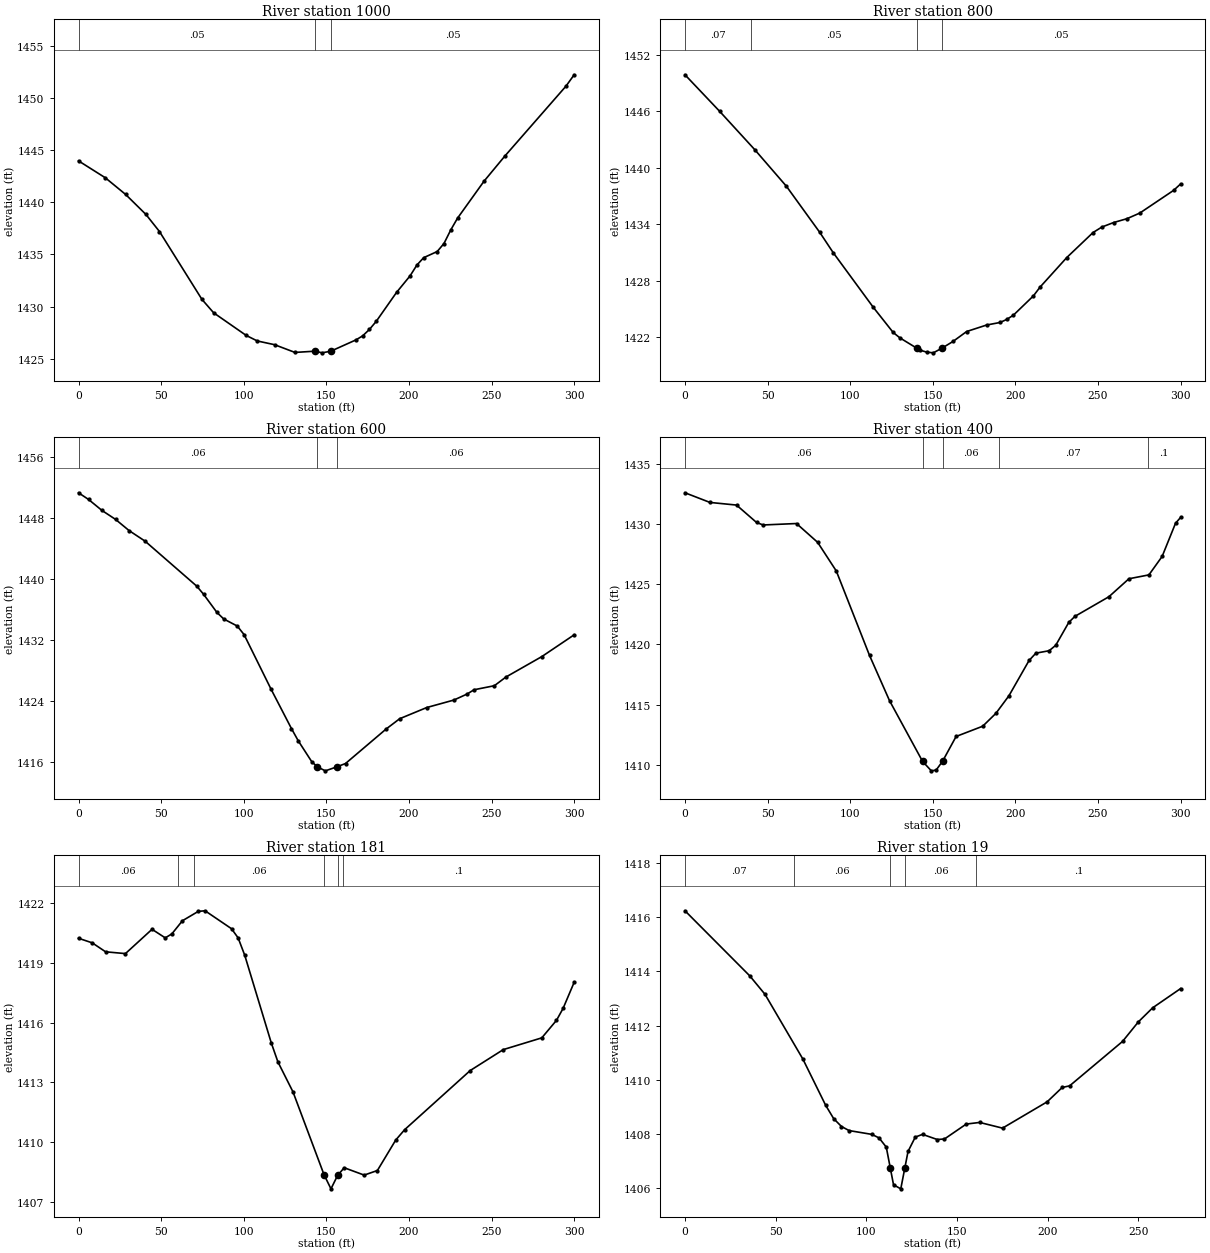
Type RM Length L Ch R = 1 ,1000    ,200,200,200
XS GIS Cut Line= 2
  2191004.386919718814.7301996412191297.05919664718748.829229232
#Sta/Elev= 30
       0 1443.98    16.2 1442.36    28.5 1440.76    40.8 1438.84      49  1437.2
    74.7 1430.69    81.8  1429.4   101.5 1427.23   108.2  1426.7   118.7 1426.34
     131  1425.6   143.3 1425.72   147.4 1425.56   152.71425.718   167.9  1426.8
     172 1427.19   176.1 1427.81   180.2 1428.58   192.5 1431.36   200.7 1432.95
   204.8 1433.98   208.9 1434.69   217.1 1435.28   221.2 1436.05   225.3 1437.35
   229.4 1438.48   245.4 1442.02   258.1 1444.45     295 1451.14     300 1452.24
#Mann= 3 ,-1,0
       0     .05       0   143.3    .045       0   152.7     .05       0
Bank Sta=143.3,152.7
XS Rating Curve= 0 ,0
Exp/Cntr(USF)=0,0
Exp/Cntr=0.3,0.1

Type RM Length L Ch R = 1 ,800     ,200,200,200
XS GIS Cut Line= 2
2191047.42875769718996.1839266962191344.36261171718953.402080773
#Sta/Elev= 30
       0 1449.89      21    1446    42.2 1441.93    61.4 1438.03    81.6 1433.12
    89.7 1430.97   113.9 1425.17     126 1422.48   130.1  1421.9   140.21420.816
   142.2  1420.6   146.2 1420.39   150.3 1420.31   155.61420.813   162.3 1421.53
   170.5 1422.58   182.6 1423.27   190.7 1423.54   194.7 1423.86   198.8 1424.32
   210.9 1426.37   214.9  1427.3   231.1 1430.45     247 1433.11   252.3 1433.69
   259.4 1434.17   267.5 1434.58   275.3 1435.18   295.8  1437.6     300 1438.28
#Mann= 4 ,-1,0
       0     .07       0      40     .05       0   140.2    .045       0
   155.6     .05       0
Bank Sta=140.2,155.6
XS Rating Curve= 0 ,0
Exp/Cntr(USF)=0,0
Exp/Cntr=0.3,0.1

Type RM Length L Ch R = 1 ,600     ,200,200,200
XS GIS Cut Line= 2
2191046.26239115719203.2493537922191339.33295555719139.142846461
#Sta/Elev= 30
       0  1451.3     6.1 1450.42    14.2 1448.98    22.4 1447.81    30.6 1446.34
    40.3 1444.95    71.6 1439.04    75.7 1437.98    83.8 1435.59    87.9 1434.74
    96.1 1433.81   100.2 1432.69   116.6  1425.5   128.9 1420.35     133 1418.75
   141.2    1416   144.61415.328   149.4 1414.81   156.21415.321   161.6 1415.77
   186.2  1420.3   194.4 1421.65   210.8 1423.12   227.2  1424.1   235.2 1424.89
   239.4 1425.45   251.7 1425.98   258.7 1427.12   280.4  1429.8     300 1432.66
#Mann= 3 ,-1,0
       0     .06       0   144.6    .045       0   156.2     .06       0
Bank Sta=144.6,156.2
XS Rating Curve= 0 ,0
Exp/Cntr(USF)=0,0
Exp/Cntr=0.3,0.1

Type RM Length L Ch R = 1 ,400     ,218.7,218.7,218.7
XS GIS Cut Line= 2
2191097.12556749719370.8595478162191395.26738699719337.521049625
#Sta/Elev= 30
       0 1432.58    15.1 1431.78    31.2 1431.56    43.3 1430.12    47.3 1429.91
    67.5 1430.03    80.3 1428.47    91.6 1426.09   111.7 1419.09   123.8 1415.34
   143.81410.306   149.1 1409.52     152 1409.58   155.91410.312   164.1 1412.37
   180.2 1413.22   188.2 1414.29   196.1 1415.75   208.3 1418.68   212.4 1419.28
   220.4 1419.48   224.4 1419.93   232.3 1421.83     236 1422.33   256.6 1423.96
   268.7 1425.45   280.8 1425.77   288.8  1427.3   296.9 1430.05     300 1430.54
#Mann= 5 ,-1,0
       0     .06       0   143.8    .045       0   155.9     .06       0
     190     .07       0     280      .1       0
Bank Sta=143.8,155.9
XS Rating Curve= 0 ,0
Exp/Cntr(USF)=0,0
Exp/Cntr=0.3,0.1

Type RM Length L Ch R = 1 ,181     ,162,162,162
XS GIS Cut Line= 2
2191119.87014383719552.7065198432191418.88777502719528.448402891
#Sta/Elev= 30
       0 1420.24     8.3 1420.01    16.4 1419.56    28.4 1419.47    44.5 1420.69
    52.5 1420.26    56.5 1420.46    62.9 1421.12    72.5 1421.59    76.6 1421.62
    92.6 1420.72    96.6 1420.26   100.6 1419.39   116.7 1414.98   120.7 1414.03
   129.8 1412.53   148.6 1408.37   152.8 1407.66   156.8 1408.33   160.8 1408.72
   172.9 1408.35   180.9 1408.58     192 1410.11   197.4 1410.63   237.1  1413.6
   257.1 1414.65   280.4 1415.24   289.3 1416.12   293.3 1416.72     300 1418.03
#Mann= 6 ,-1,0
       0     .06       0      60     .05       0      70     .06       0
   148.6    .045       0   156.8     .06       0     160      .1       0
Bank Sta=148.6,156.8
XS Rating Curve= 0 ,0
Exp/Cntr(USF)=0,0
Exp/Cntr=0.3,0.1

Type RM Length L Ch R = 1 ,19      ,,,
XS GIS Cut Line= 4
 2191130.3493021719648.7949013472191225.71509991719680.583500616
2191311.54431794719675.0204957442191394.98939102719651.179046292
#Sta/Elev= 30
       0 1416.24    35.7 1413.84    44.1 1413.16      65 1410.77    77.6 1409.06
      82 1408.57    86.3 1408.28    90.5 1408.13     103 1407.99     107 1407.86
     111 1407.52   113.21406.754     115 1406.13     119 1405.98   121.21406.739
     123 1407.36     127 1407.89     131 1407.99   139.1  1407.8   143.1 1407.82
   155.1 1408.37   162.5 1408.43   175.1 1408.22   199.7 1409.19     208 1409.72
   212.1 1409.78   241.3 1411.42     250 1412.14   257.9 1412.66273.3179 1413.37
#Mann= 5 ,-1,0
       0     .07       0      60     .06       0   113.2    .045       0
   121.2     .06       0  160.52      .1       0
Bank Sta=113.2,121.2
XS Rating Curve= 0 ,0
Exp/Cntr(USF)=0,0
Exp/Cntr=0.3,0.1
LCMann Table=0

Chan Stop Cuts=-1
Use User Specified Reach Order=0
Composite Channel Slope=5